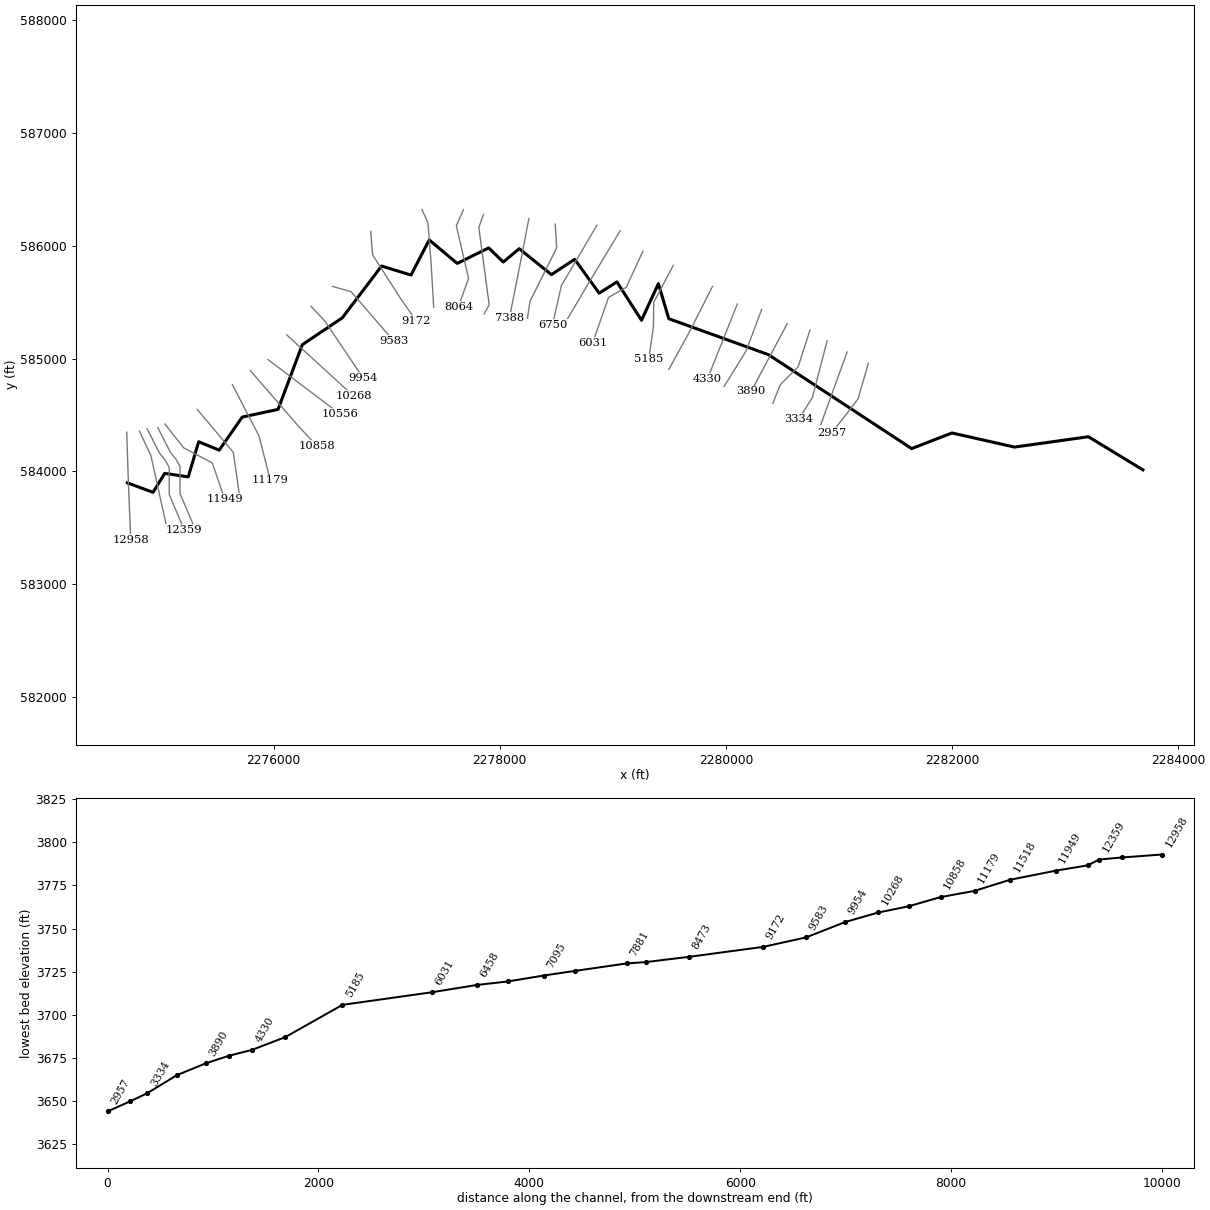
--- LAMBERTRN.prj (project) ---

Proj Title=LAMBERTRN
Current Plan=p01
Default Exp/Contr=0,0
English Units
Geom File=g01
Flow File=f01
Plan File=p01
BEGIN DESCRIPTION:
----------MODEL BY WOOD PLC 2022----------
AFH study
Randolph County, WV
HEC-RAS Version: RAS 6.2
Vertical Datum: NAVD88
Projection: NAD 1983 StatePlane West Virginia S FIPS 4702 (US Feet)
Terrain: 1-meter LIDAR (FEMA Region III 3DEP collected 2016-2018)
Land Use: 2019 NLCD
Hydrologic Method:
WV SIR2010-5033 regression equations
Additional Model Notes:
None
END DESCRIPTION:
DSS Export Rating Curves= 0
DSS Export Rating Curve Sorted= 0
DSS Export Volume Flow Curves= 0
DXF OffsetX= 0
DXF OffsetY= 0
DXF ScaleX= 0
DXF ScaleY= 0

--- LAMBERTRN.p01 (plan) ---

Plan Title=Floodplain
Program Version=6.20
Short Identifier=Floodplain
Geom File=g01
Flow File=f01
Subcritical Flow
K Sum by GR= 0
Std Step Tol= 0.01
Critical Tol= 0.01
Num of Std Step Trials= 20
Max Error Tol= 0.3
Flow Tol Ratio= 0.001
Split Flow NTrial= 30
Split Flow Tol= 0.02
Split Flow Ratio= 0.02
Log Output Level= 0
Friction Slope Method= 1
Unsteady Friction Slope Method= 2
Unsteady Bridges Friction Slope Method= 1
Parabolic Critical Depth
Global Vel Dist= 0 , 0 , 0
Global Log Level= 0
CheckData=True
Encroach Param=-1 ,0,0, 0
Mapping Interval=1HOUR
Computation Time Step Use Courant=        0
Computation Time Step Use Time Series=    0
Computation Time Step Count To Double=0
Computation Time Step Max Doubling=0
Computation Time Step Max Halving=0
Computation Time Step Residence Courant=0
Run HTab= 0
Run UNet= 0
Run Sediment= 0
Run PostProcess= 0
Run WQNet= 0
Run RASMapper=-1
UNET Theta= 0
UNET Theta Warmup= 0
UNET ZTol= 0
UNET ZSATol= 0
UNET MxIter= 0
UNET Max Iter WO Improvement= 0
UNET MaxInSteps= 0
UNET DtIC= 0
UNET DtMin= 0
UNET MaxCRTS= 0
UNET WFStab= 0
UNET SFStab= 0
UNET WFX= 1
UNET SFX= 1
UNET Gravity=32.174
UNET 1D Methodology=Finite Difference
UNET DSS MLevel= 1
UNET Pardiso=0
UNET DZMax Abort= 0
UNET Use Existing IB Tables= 0
UNET Froude Reduction=False
UNET Froude Limit= 0
UNET Froude Power= 0
UNET D1 Cores= 0
UNET WindReference=Eulerian
UNET WindDragFormulation=Hsu (1988)
UNET D2 Coriolis=0
UNET D2 Cores= 0
UNET D2 Theta= 1
UNET D2 Theta Warmup= 1
UNET D2 Z Tol= 0.01
UNET D2 Volume Tol= 0.01
UNET D2 Max Iterations= 20
UNET D2 Equation= 0
UNET D2 RampUpFraction=0.1
UNET D2 TimeSlices= 1
UNET D2 Turbulence Formulation=Non-Conservative (original)
UNET D2 Eddy Viscosity=0.3
UNET D2 Transverse Eddy Viscosity=0.1
UNET D2 Smagorinsky Mixing=0
UNET D2 BCVolumeCheck=0
UNET D2 Cores=0
UNET D2 SolverType=PARDISO (Direct)
UNET D2 Minimum Iterations= 2147483647
UNET D2 Maximum Iterations= 2147483647
UNET D2 Restart Number= 10
UNET D2 Relaxation Coeff=1.3
UNET D2 SOR Precondition Iterations= 10
UNET D2 ILUT Maximum Fill= 8
UNET D2 ILUT Tolerance=1E-08
UNET D1D2 MaxIter= 0
UNET D1D2 ZTol=0.01
UNET D1D2 QTol=0.1
UNET D1D2 MinQTol=1
Write IC File= 0
Write IC File at Fixed DateTime=0
Write IC File at Sim End=0
Echo Input=False
Echo Parameters=False
Echo Output=False
Write Detailed= 0
HDF Write Warmup=0
HDF Write Time Slices=0
HDF Flush=0
HDF Compression= 1
HDF Chunk Size= 1
HDF Spatial Parts= 1
HDF Use Max Rows=0
HDF Fixed Rows= 1
Calibration Method= 0
Calibration Iterations= 20
Calibration Max Change=0.05
Calibration Tolerance=0.2
Calibration Maximum=1.5
Calibration Minimum=0.5
Calibration Optimization Method= 1
WQ AD Non Conservative
WQ ULTIMATE=-1
WQ Max Comp Step=1HOUR
WQ Output Interval=15MIN
WQ Output Selected Increments= 0
WQ Output face flow=0
WQ Output face velocity=0
WQ Output face area=0
WQ Output face dispersion=0
WQ Output cell volume=0
WQ Output cell surface area=0
WQ Output cell continuity=0
WQ Output cumulative cell continuity=0
WQ Output face conc=0
WQ Output face dconc_dx=0
WQ Output face courant=0
WQ Output face peclet=0
WQ Output face adv mass=0
WQ Output face disp mass=0
WQ Output cell mass=0
WQ Output cell source sink temp=0
WQ Output nsm pathways=0
WQ Output nsm derived pathways=0
WQ Create Restart=0
WQ Fixed Restart=0
WQ System Summary=0
WQ Write To DSS=0
Sorting and Armoring Iterations= 10
XS Update Threshold= 0.02
Bed Roughness Predictor= 0
Hydraulics Update Threshold= 0.02
Energy Slope Method= 1
Volume Change Method= 1
Sediment Retention Method= 0
Sediment TS Multiplier= 1
Warm Up Method= 0
XS Weighting Method= 0
Number of US Weighted Cross Sections= 1
Number of DS Weighted Cross Sections= 1
Upstream XS Weight=0
Main XS Weight=1
Downstream XS Weight=0
Number of DS XS's Weighted with US Boundary= 1
Upstream Boundary Weight= 1
Weight of XSs Associated with US Boundary= 0
Number of US XS's Weighted with DS Boundary= 1
Downstream Boundary Weight= 0.5
Weight of XSs Associated with DS Boundary= 0.5
Percentile Method= 0
Sediment Output Level= 3
Mass or Volume Output= 0
Output Increment Type= 1
Profile and TS Output Increment= 1
Transport Output Increment 1
XS Output Flag= 0
XS Output Increment= 10
Read HDF5 Sediment Hotstart= 0
Sediment Hotstart Type= 0
Write Gradation File= 0
Read Gradation Hotstart= 0
Write HDF5 File= 1
Write Binary Output= 1
Write DSS Sediment File= 0
DSS Sediment Output Type= 1
SV Curve= 0
Specific Gage Flag= 0
Subcell Erosion Methods= 0
Subcell Deposition Methods= 0
Advection Scheme= 1
Matrix Solver= 0
Implicit Weighting Factor= 1
Maximum Outer Loop Convergence Iterations= 5
Convergence Maximum Absolute= 0.001
Convergence RMSE= 0.0001
Grain Fractions Max Abs Error= 0.001
Max Subgrid Regions= 1
Max Subgrid Length Scale= 3.402823E+38
Initial Layer Thickness= 3.402823E+38
Min Layer Thickness= 3.402823E+38
Max Layer Thickness= 3.402823E+38
Number of Layers= 5

--- LAMBERTRN.f01 (steady flow) ---

Flow Title=Flow
Program Version=6.20
Number of Profiles= 1
Profile Names=P100yr
River Rch & RM=LAMBERTRN,Main,12958
     436
River Rch & RM=LAMBERTRN,Main,9172
     490
River Rch & RM=LAMBERTRN,Main,8473
     555
River Rch & RM=LAMBERTRN,Main,7095
     625
River Rch & RM=LAMBERTRN,Main,4643
     698
Boundary for River Rch & Prof#=LAMBERTRN,Main            , 1
Up Type= 0
Dn Type= 3
Dn Slope=0.02419
DSS Import GetInterval= 0
DSS Import GetPeak= 0
DSS Import FillOption= 0

--- LAMBERTRN.g01 (geometry) ---

Geom Title=Geometry
Program Version=6.20

River Reach=LAMBERTRN       ,Main
Reach XY= 30
     2274707.156      583899.115     2274934.803       583815.13
     2275037.885      583983.099     2275246.001      583952.066
     2275338.125      584263.042     2275519.784      584188.845
     2275723.258      584481.667     2276040.129      584550.015
     2276254.682       585123.16     2276607.894      585360.747
     2276955.498      585820.087     2277215.914      585740.399
     2277376.678      586051.511     2277624.595      585843.525
     2277903.202      585980.746      2278031.78      585855.328
     2278172.779       585973.83     2278457.324      585744.061
     2278663.052      585879.999     2278879.719      585579.478
      2279036.49      585679.478     2279254.199      585339.374
      2279403.45      585664.163     2279495.269      585353.411
     2280377.115      585034.686     2281642.909      584202.734
     2281999.511      584340.936     2282552.115      584215.936
     2283205.898      584307.708      2283687.75      584014.182

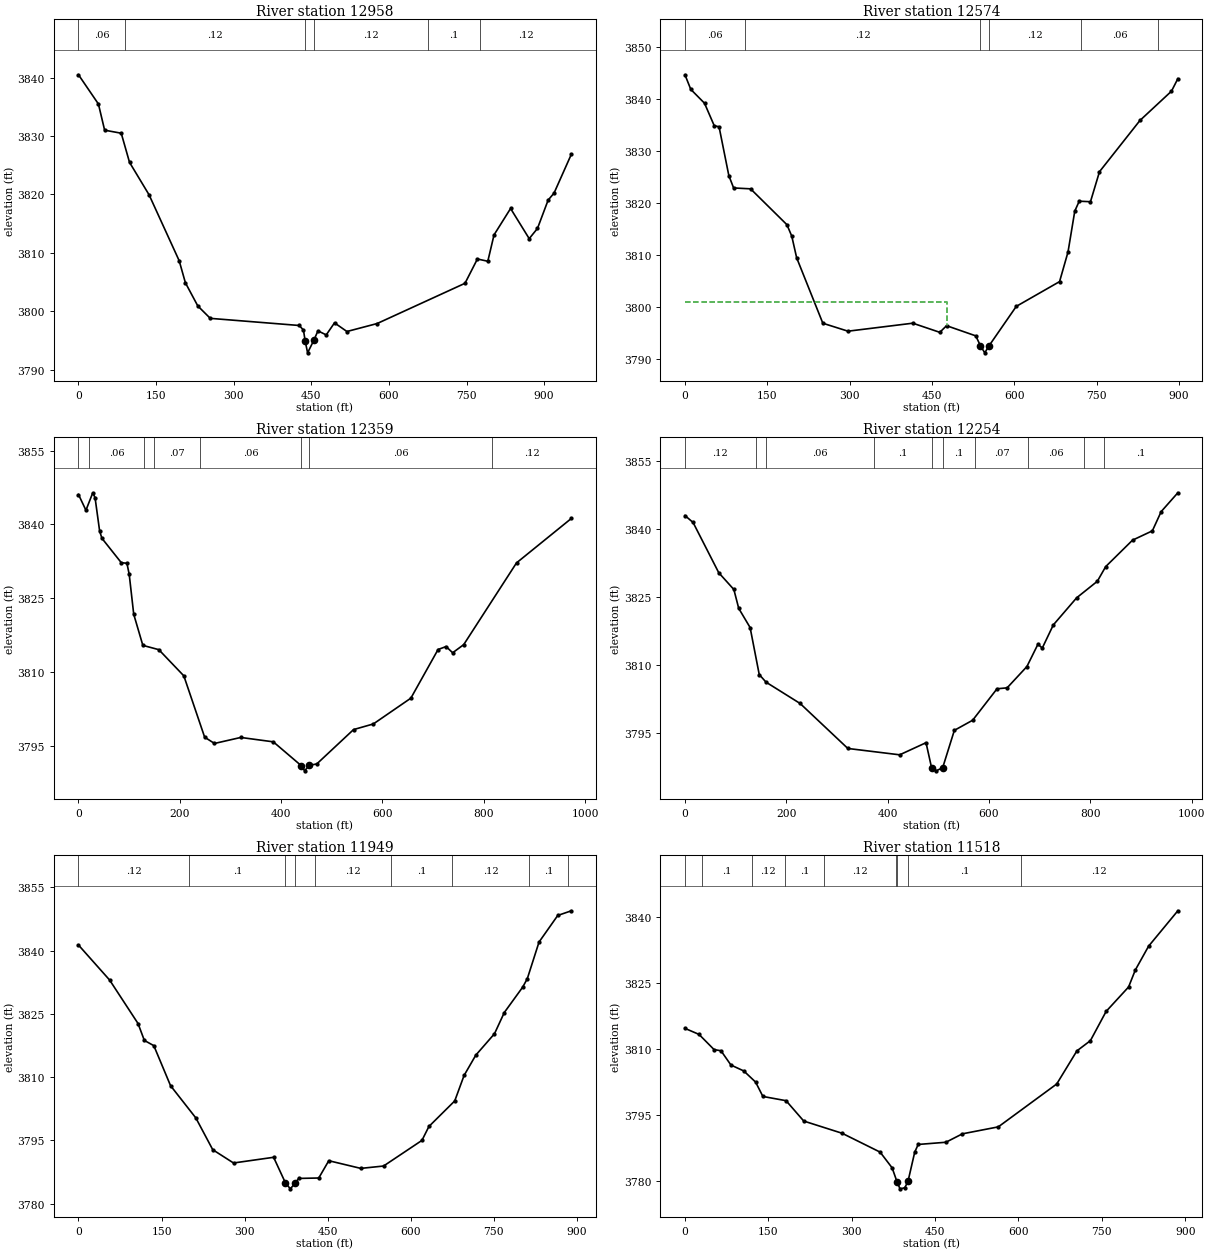
Type RM Length L Ch R = 1 ,12958   ,378.2,383.8,380.4
XS GIS Cut Line= 3
     2274701.902      584347.699     2274716.485      583902.232
      2274737.49      583395.748
#Sta/Elev= 30
       0 3840.47    38.5 3835.47    50.5 3830.99    82.6 3830.47    98.6 3825.49
   136.4 3819.93   194.6 3808.65   206.6 3804.88   230.6 3800.91   254.7 3798.79
   426.7 3797.57   434.8 3796.78     4383794.964   442.8 3792.89   454.8 3795.03
   462.8 3796.65   478.8 3795.96   494.8 3798.02   518.8 3796.54   577.1  3797.9
     747 3804.79     771 3808.95   791.1 3808.56   803.1 3813.07   835.1 3817.59
   871.1 3812.43   887.1 3814.18   907.7 3819.03   919.1 3820.22   952.6 3826.88
#Mann= 6 ,-1,0
       0     .06       0      90     .12       0     438    .045       0
   454.8     .12       0  675.71      .1       0  775.71     .12       0
Bank Sta=438,454.8
XS Rating Curve= 0 ,0
Exp/Cntr=0.3,0.1

Type RM Length L Ch R = 1 ,12574   ,214.5,214.6,213.6
BEGIN DESCRIPTION:
Structure XS 4
END DESCRIPTION:
XS GIS Cut Line= 3
2274814.34554341584357.492103872   2274916.25546584138.537134558
2275057.51673053 583497.81637182
#Sta/Elev= 30
       0 3844.73    10.6 3841.92    35.6 3839.25    53.3 3834.92    62.1 3834.71
    79.9 3825.31    88.6 3822.93   119.5 3822.76   185.7 3815.85   194.5 3813.65
   203.4 3809.48   251.1 3796.87   296.9 3795.34   414.9 3796.88   464.1 3795.12
   476.4  3796.4   529.6 3794.44   538.23792.514     546 3791.17   553.7 3792.52
   603.4 3800.12   682.2 3804.89   697.6  3810.6   709.9 3818.47     718 3820.38
   738.5 3820.28   754.9 3826.06   828.6 3835.93     886 3841.57   897.6 3843.97
#Mann= 6 ,-1,0
       0     .06       0     110     .12       0   538.2    .045       0
   553.7     .12       0  721.51     .06       0  861.51     .12       0
#XS Ineff= 2 , 0
          476.75 3800.97
Permanent Ineff=
       F       F
Bank Sta=538.2,553.7
XS Rating Curve= 0 ,0
Exp/Cntr(USF)=0,0
Exp/Cntr=0.3,0.1

Type RM Length L Ch R = 1 ,12359   ,103.8,104.9,106.6
BEGIN DESCRIPTION:
Structure XS 3
END DESCRIPTION:
XS GIS Cut Line= 6
2274881.78708252584378.294235331 2274991.9574636584162.562635196
2275042.52057668584098.4494440332275077.78170217584035.648823966
2275078.23927828583794.8404804182275209.45833712583485.460389519
#Sta/Elev= 30
       0 3846.07    14.7 3842.88    28.2 3846.43    32.7 3845.43    41.7 3838.67
    46.2 3837.19    84.4 3832.24    95.6 3832.11   100.1 3829.86     109 3821.76
     127 3815.44   158.5 3814.57   207.9 3809.25     249 3796.79   268.4 3795.52
   320.3 3796.74   384.5 3795.85   439.8    3791   446.4 3789.96  455.11 3791.05
   470.4 3791.37   542.9 3798.34   581.9 3799.48     656 3804.72   709.7  3814.6
   725.5  3815.2   738.5 3813.94   760.3 3815.59   864.5 3832.19   972.8 3841.22
#Mann= 8 ,-1,0
       0     .12       0      20     .06       0     130     .12       0
     150     .07       0     240     .06       0   439.8    .045       0
  455.11     .06       0  816.79     .12       0
Bank Sta=439.8,455.11
XS Rating Curve= 0 ,0
Exp/Cntr=0.3,0.1

Type RM Length L Ch R = 1 ,12254   ,292.5,305.2,314.8
BEGIN DESCRIPTION:
Structure XS 2
END DESCRIPTION:
XS GIS Cut Line= 6
2274976.91137878584387.7040798912275087.08175987584171.972479757
2275137.64487294584107.8592885942275172.90599843584045.058668527
2275173.36357454583804.2503249792275304.58263338 583494.87023408
#Sta/Elev= 30
       0 3842.87      16 3841.35    66.7 3830.27    96.5 3826.58   106.1 3822.42
   128.6 3818.19   146.6 3807.84     160 3806.16   227.3 3801.46   321.5 3791.55
   423.8 3790.15   475.8 3792.82  486.76  3787.3   495.8 3786.62  508.66 3787.31
   531.7 3795.54   567.8 3797.77   615.9  3804.7   635.9 3804.91   674.9  3809.6
   696.6  3814.5   705.3 3813.69     727 3818.77   773.1 3824.75   813.9 3828.39
   830.4 3831.62   883.4 3837.45   922.5  3839.5   939.9 3843.74   972.8 3847.89
#Mann= 10 ,-1,0
       0     .12       0     140     .07       0     160     .06       0
  373.89      .1       0  486.76    .045       0  508.66      .1       0
  572.79     .07       0  676.79     .06       0  786.79     .12       0
  826.79      .1       0
Bank Sta=486.76,508.66
XS Rating Curve= 0 ,0
Exp/Cntr=0.3,0.1

Type RM Length L Ch R = 1 ,11949   ,427.5,431.6,423.4
BEGIN DESCRIPTION:
Structure XS 1
END DESCRIPTION:
XS GIS Cut Line= 4
2275040.14703989584420.0217141192275204.94870044584209.647727803
2275458.48271618584075.6609124122275567.43586683583757.946899727
#Sta/Elev= 30
       0 3841.34    56.2 3833.04   107.5 3822.73   118.9 3818.72     136 3817.48
   166.2 3807.99   211.9 3800.33   242.4  3792.8   279.9 3789.65   352.3    3791
   373.6 3784.94   382.5 3783.52   391.3 3784.89   397.6 3785.99   433.8 3786.09
   451.9 3790.19   509.7 3788.37   550.8 3788.93   620.1 3795.01   632.7 3798.31
   679.3 3804.37   696.2 3810.42   717.3 3815.22   751.1 3820.31   768.8 3825.34
   801.9 3831.34   810.3 3833.35   831.5 3842.05   865.3 3848.36   889.9 3849.47
#Mann= 9 ,-1,0
       0     .12       0     200      .1       0   373.6    .045       0
   391.3      .1       0  427.24     .12       0     564      .1       0
     674     .12       0     814      .1       0     884     .12       0
Bank Sta=373.6,391.3
XS Rating Curve= 0 ,0
Exp/Cntr=0.3,0.1

Type RM Length L Ch R = 1 ,11518   ,338,338.6,334.9
XS GIS Cut Line= 3
2275326.52639382584548.5587473692275644.34809542584169.647661327
2275699.92873799  583781.4818119
#Sta/Elev= 30
       0 3814.69    25.3 3813.32    52.4 3809.87    64.8 3809.61    82.7 3806.37
   105.8 3805.03   127.1  3802.5   140.2 3799.24   181.9 3798.28   213.7 3793.66
   282.7 3790.89   351.1 3786.61   372.7 3783.04   381.53779.877   386.9 3778.28
   395.4 3778.52   401.2 3779.95   413.4 3786.63   419.6 3788.35   469.4 3788.85
   499.1 3790.76   563.7 3792.34   668.8 3802.07   705.1 3809.58   729.4  3811.9
   757.7 3818.54   798.1 3824.08   810.2 3827.93   834.1 3833.34   886.7 3841.37
#Mann= 9 ,-1,0
       0     .12       0      30      .1       0     120     .12       0
     180      .1       0     250     .12       0     380      .1       0
   381.5    .045       0   401.2      .1       0  604.55     .12       0
Bank Sta=381.5,401.2
XS Rating Curve= 0 ,0
Exp/Cntr=0.3,0.1

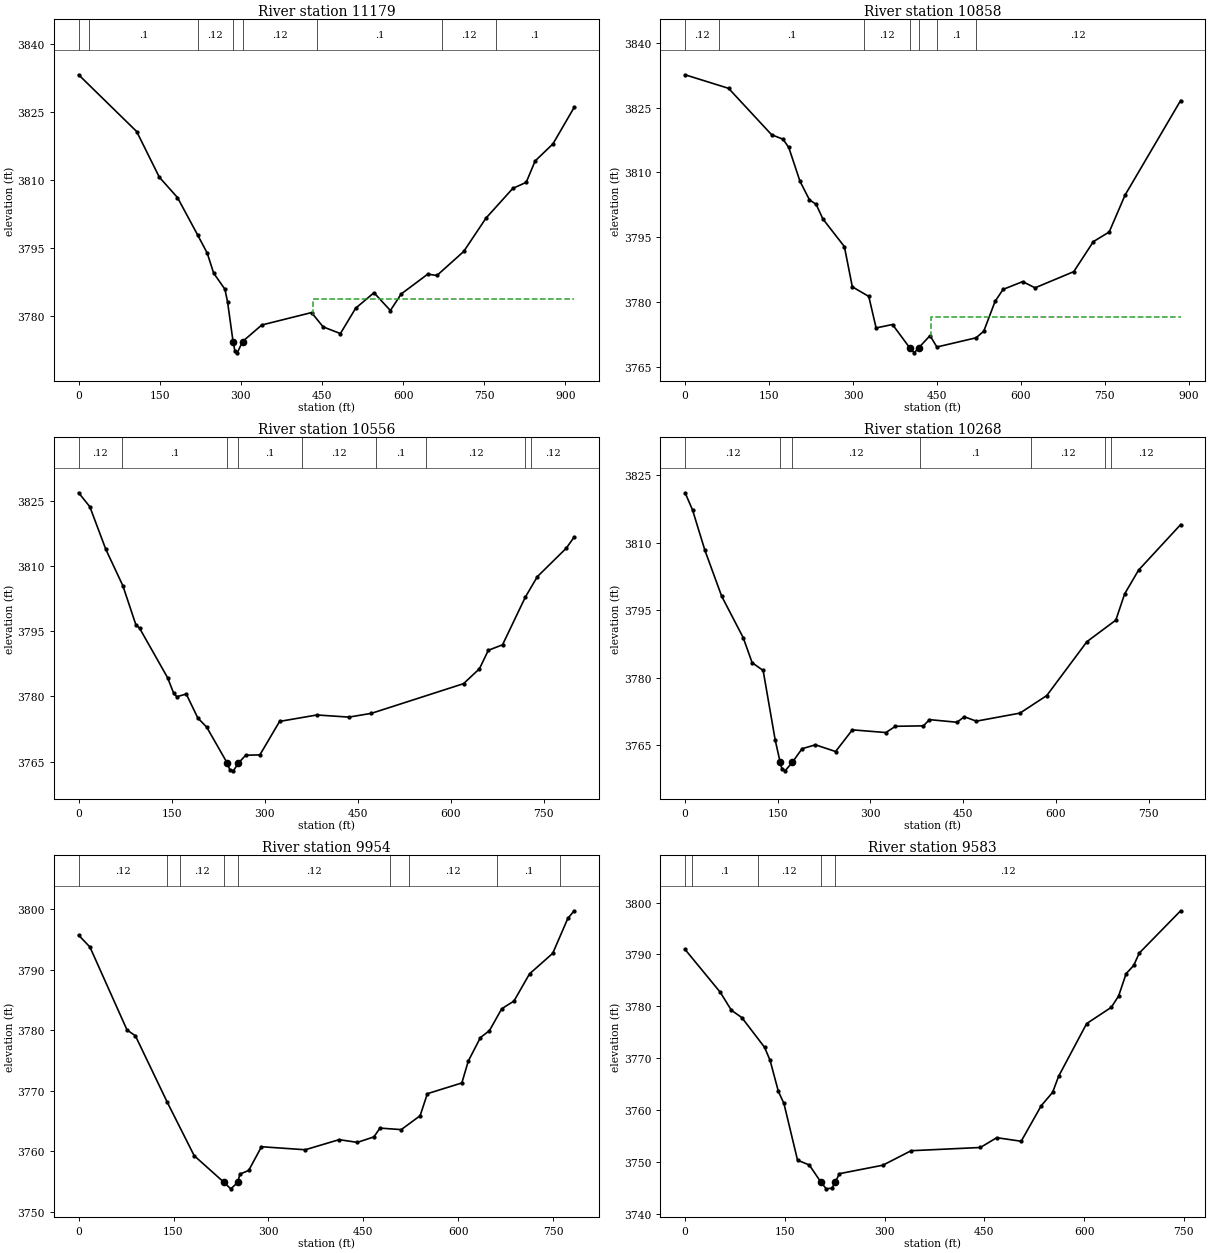
Type RM Length L Ch R = 1 ,11179   ,319.2,321.6,321.9
XS GIS Cut Line= 3
2275636.07255378584769.6590027462275871.83977826584314.802811899
2275971.31854439583923.175747368
#Sta/Elev= 30
       0 3833.12   107.3 3820.61   149.2 3810.54   182.8 3806.05     220 3797.81
   237.8  3793.8   249.7 3789.38   270.5 3785.83   275.4 3783.04  285.58 3774.29
   288.9 3772.28   293.4  3771.8   303.1 3774.29   338.7 3777.94   430.7 3780.68
   452.2 3777.52   484.1 3776.05   512.3 3781.64   546.2 3785.06   576.5 3781.13
   596.5 3784.78   645.6 3789.15   662.6 3788.86   712.1 3794.15   753.4 3801.52
   802.9 3808.06   827.7  3809.4   844.2 3814.11   877.2 3817.89   916.4 3825.93
#Mann= 8 ,-1,0
       0     .12       0      20      .1       0     220     .12       0
  285.58    .045       0   303.1     .12       0     440      .1       0
  672.33     .12       0  772.33      .1       0
#XS Ineff= 2 , 0
                          433.94         3783.64
Permanent Ineff=
       F       F
Bank Sta=285.58,303.1
XS Rating Curve= 0 ,0
Exp/Cntr=0.3,0.1

Type RM Length L Ch R = 1 ,10858   ,299.6,302,301.3
XS GIS Cut Line= 3
2275794.96781854584893.511002746 2276220.6283508584401.400082151
2276380.72153501584229.265623799
#Sta/Elev= 30
       0 3832.63    77.7 3829.49   154.7 3818.73     175 3817.71   185.3 3815.79
   205.3 3807.97   222.3 3803.66   234.2 3802.62   246.4 3799.21   284.7 3792.83
   298.9 3783.51   328.3 3781.29   341.4 3773.99   370.7 3774.78  401.713769.346
   409.5 3768.22   417.6  3769.4   437.8 3772.21     450 3769.57     520  3771.7
   533.8 3773.22   554.1 3780.15   568.3 3782.91   603.4 3784.72   625.5 3783.28
   694.7 3787.03   729.7 3793.98     758 3796.21   786.4 3804.77   885.7 3826.67
#Mann= 7 ,-1,0
       0     .12       0      60      .1       0     320     .12       0
  401.71    .045       0   417.6     .12       0     450      .1       0
     520     .12       0
#XS Ineff= 2 , 0
                          439.71         3776.55
Permanent Ineff=
       F       F
Bank Sta=401.71,417.6
XS Rating Curve= 0 ,0
Exp/Cntr=0.3,0.1

Type RM Length L Ch R = 1 ,10556   ,289.3,287.8,286.5
XS GIS Cut Line= 2
 2275949.8728316584992.188904908 2276586.8563435584509.986433283
#Sta/Elev= 30
       0 3826.86    18.1 3823.64    43.8 3813.86    71.3 3805.48    92.3 3796.49
    98.2 3795.72   143.4 3784.33   153.4 3780.69   158.4 3779.95   173.5 3780.57
   192.2 3775.05   206.5 3772.95  239.763764.636   243.6 3763.19   249.4  3762.9
   257.63764.684   269.3 3766.49   292.2 3766.57     324 3774.27   384.2 3775.75
   435.8 3775.26   472.1 3776.13   620.5 3782.95   646.2 3786.38   660.5 3790.63
   683.4 3791.89   720.3  3802.9   739.6 3807.58   786.2 3814.12   798.9 3816.68
#Mann= 9 ,-1,0
       0     .12       0      70      .1       0  239.76    .045       0
   257.6      .1       0     360     .12       0     480      .1       0
     560     .12       0     720      .1       0     730     .12       0
Bank Sta=239.76,257.6
XS Rating Curve= 0 ,0
Exp/Cntr(USF)=0,0
Exp/Cntr=0.3,0.1

Type RM Length L Ch R = 1 ,10268   ,315.5,313.5,310.9
XS GIS Cut Line= 2
2276116.56010575585210.4698591412276707.90305449 584668.73621818
#Sta/Elev= 30
       0 3821.09      12 3817.29      32 3808.33    59.1 3798.13    94.1 3788.87
   108.5 3783.32   126.3  3781.6   145.9 3766.08  153.843761.217   156.8 3759.67
   161.8 3759.29   173.6 3761.19   189.3 3764.21     211 3765.07   243.6 3763.58
   270.7  3768.4     325  3767.8   340.4 3769.19   385.7 3769.29   395.5 3770.67
   440.1 3770.09   451.9 3771.31   471.4 3770.33     542 3772.12   585.4 3776.03
   650.4 3788.01   697.1 3792.78   711.3 3798.59   733.9  3803.9     802 3814.02
#Mann= 7 ,-1,0
       0     .12       0  153.84    .045       0   173.6     .12       0
     380      .1       0     560     .12       0     680      .1       0
     690     .12       0
Bank Sta=153.84,173.6
XS Rating Curve= 0 ,0
Exp/Cntr(USF)=0,0
Exp/Cntr=0.3,0.1

Type RM Length L Ch R = 1 ,9954    ,369.3,371.6,372.1
XS GIS Cut Line= 3
2276331.96259405585462.7744919912276455.96004302585330.089052403
2276791.01544622584830.123596796
#Sta/Elev= 30
       0 3795.73    17.9 3793.76    76.5 3780.06    89.8 3779.09     140 3768.14
   182.7 3759.28  229.763754.878   240.5  3753.8   251.6 3754.85   254.9 3756.23
   268.9 3756.84   289.1 3760.76   358.3 3760.26   411.9 3761.93   440.7 3761.48
   466.8 3762.38   476.5 3763.84   510.1 3763.59   539.9 3765.88   551.4 3769.53
   605.9  3771.3   616.1 3774.92   635.3 3778.81   649.5 3779.94     669 3783.57
   688.3 3784.84   712.9 3789.33   749.6 3792.73   773.4 3798.49   783.5 3799.76
#Mann= 9 ,-1,0
       0     .12       0     140      .1       0     160     .12       0
  229.76    .045       0   251.6     .12       0  491.61      .1       0
  521.61     .12       0  661.61      .1       0  761.61     .12       0
Bank Sta=229.76,251.6
XS Rating Curve= 0 ,0
Exp/Cntr=0.3,0.1

Type RM Length L Ch R = 1 ,9583    ,406.7,410.5,406
XS GIS Cut Line= 3
2276521.25432929585639.5840578952276686.21554439585592.746436842
2277060.75115995585158.157362929
#Sta/Elev= 30
       0 3790.96    52.9 3782.72    69.6 3779.26    85.3 3777.85   119.5 3772.13
   127.8 3769.61   140.3 3763.62   148.6 3761.32   169.1  3750.4   186.8 3749.47
   203.8 3746.25   212.3 3744.88   220.8 3745.02  226.053746.223   232.1  3747.8
   297.4 3749.43   339.9 3752.22   444.1 3752.84   468.6 3754.73   505.4 3754.04
   535.6 3760.89   552.6 3763.44   561.7 3766.55   603.9  3776.7   640.9 3779.82
   651.9    3782   663.2  3786.3   674.6 3787.88     683 3790.27   745.2 3798.41
#Mann= 5 ,-1,0
       0     .12       0      10      .1       0     110     .12       0
   203.8    .045       0  226.05     .12       0
Bank Sta=203.8,226.05
XS Rating Curve= 0 ,0
Exp/Cntr=0.3,0.1

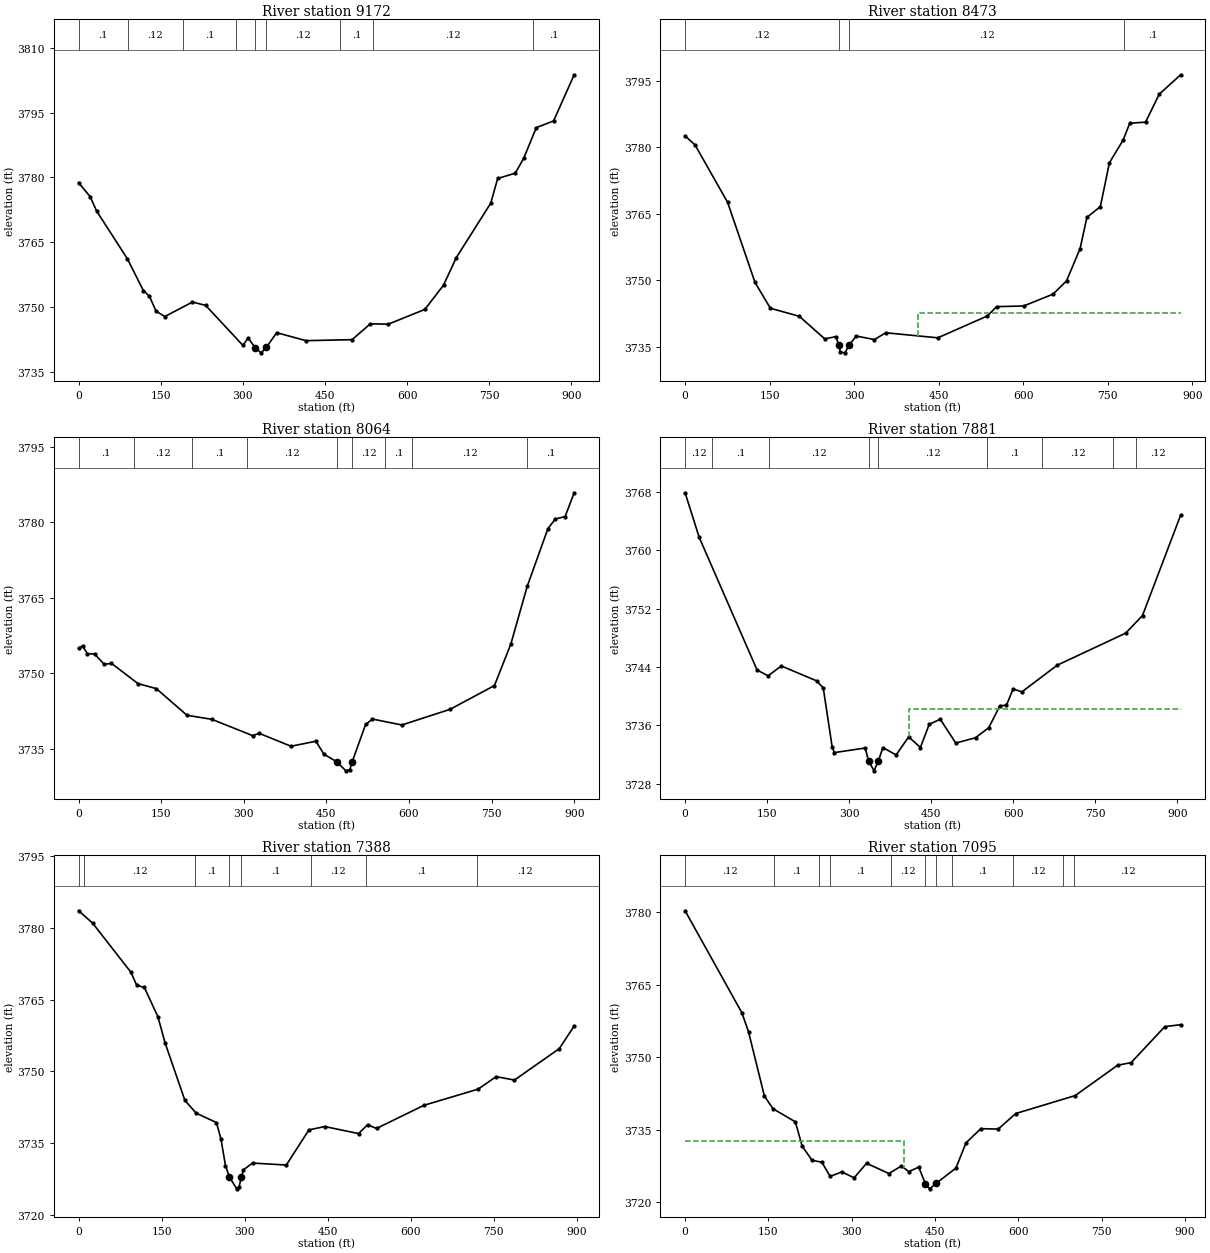
Type RM Length L Ch R = 1 ,9172    ,699.7,699.4,691.5
XS GIS Cut Line= 4
2276859.41210755586125.9991935932276876.57470094585918.890774244
2277124.94858467585530.0825350112277260.42549863585337.100935469
#Sta/Elev= 30
       0 3778.74    20.9 3775.54    32.9 3772.17    89.1 3761.11   118.2 3753.77
   129.3 3752.45   141.3 3749.01   157.4 3747.75   207.8  3751.1   231.9 3750.34
     300 3741.06   309.5 3742.78  322.233740.564   333.3 3739.34   342.8  3740.6
   361.7 3744.01   415.1 3742.16   499.4 3742.39   532.6 3746.05   565.8 3745.99
   632.3  3749.4   666.4 3755.01   689.8 3761.41   752.6 3773.99   765.3 3779.72
   797.4 3780.95   812.9 3784.42   835.8 3791.49   867.4 3793.06     905 3803.74
#Mann= 9 ,-1,0
       0      .1       0      90     .12       0     190      .1       0
  287.82     .12       0  322.23    .045       0   342.8     .12       0
  477.82      .1       0  537.82     .12       0  829.19      .1       0
Bank Sta=322.23,342.8
XS Rating Curve= 0 ,0
Exp/Cntr=0.3,0.1

Type RM Length L Ch R = 1 ,8473    ,399.7,408.6,411.4
XS GIS Cut Line= 4
2277313.05858622586321.3404417692277366.03349773586199.885090717
 2277393.5805249585844.3559501292277416.39998264585455.166188191
#Sta/Elev= 30
       0 3782.56    17.6 3780.53    75.4 3767.57     124 3749.49   151.3 3743.67
   202.7 3741.85   247.6 3736.77   267.6 3737.27   272.3 3735.36   275.6 3733.75
   283.7 3733.61  290.723735.347   303.7  3737.4   335.8  3736.6   355.9 3738.14
   448.2    3737   536.4 3741.94   552.4 3744.03   600.5 3744.18   652.6 3746.85
   676.6 3749.85   700.6 3757.12   712.7 3764.17   736.6  3766.6   752.7 3776.51
   776.8 3781.57   788.8 3785.42   816.8 3785.66   840.9 3791.95     879 3796.35
#Mann= 4 ,-1,0
       0     .12       0   272.3    .045       0  290.72     .12       0
   779.1      .1       0
#XS Ineff= 2 , 0
                          412.27         3742.67
Permanent Ineff=
       F       F
Bank Sta=272.3,290.72
XS Rating Curve= 0 ,0
Exp/Cntr=0.3,0.1

Type RM Length L Ch R = 1 ,8064    ,181.6,183.4,183.9
XS GIS Cut Line= 4
 2277679.7333211586319.7023381162277616.74557302586176.859174701
2277724.73969222585710.7212796342277635.31414119585460.901840046
#Sta/Elev= 30
       0 3754.94     7.1 3755.42    15.9 3753.86      29 3753.81    46.5 3751.74
    59.6 3751.95   107.8 3747.92   141.1 3746.92   196.8 3741.62     242 3740.81
   315.9 3737.58   328.2 3738.02   385.7 3735.46   430.9 3736.46   445.4 3733.89
  468.57 3732.38   485.4 3730.57   492.5 3730.82496.79853732.396   521.2 3739.79
   533.5 3740.87   586.9 3739.69   674.5  3742.8   755.1 3747.53   784.9 3755.79
   814.6 3767.26   852.1 3778.71   865.7 3780.67   883.4 3781.13   899.9 3785.87
#Mann= 9 ,-1,0
       0      .1       0     100     .12       0  206.11      .1       0
  306.11     .12       0  468.57    .045       0496.7985     .12       0
  556.11      .1       0  606.11     .12       0   814.6      .1       0
Bank Sta=468.57,496.7985
XS Rating Curve= 0 ,0
Exp/Cntr=0.3,0.1

Type RM Length L Ch R = 1 ,7881    ,489,492.2,481.1
XS GIS Cut Line= 4
2277856.86010895586277.4528053242277815.46315168586162.132710083
2277907.12784277585476.1259896722277862.77395999585396.289000658
#Sta/Elev= 30
       0  3767.9    25.8 3761.78   131.6  3743.6   151.7  3742.8   175.9 3744.15
   240.5 3742.11   252.6 3741.14   268.8 3733.09   272.8 3732.27   329.3  3732.9
  335.373731.148   345.4 3729.77   353.5 3731.16   361.6 3732.96   385.8 3731.95
   408.8 3734.43   430.2 3732.97   446.3 3736.14   466.5 3736.85   494.8 3733.58
   531.1 3734.31   555.3  3735.7   575.5 3738.69   587.6 3738.77   599.7    3741
   615.8  3740.6   680.4 3744.26   805.5 3748.65   836.3 3751.07     906 3764.83
#Mann= 9 ,-1,0
       0     .12       0      50      .1       0  152.53     .12       0
  335.37    .045       0   353.5     .12       0  552.53      .1       0
  652.53     .12       0  782.53      .1       0  824.63     .12       0
#XS Ineff= 2 , 0
                          408.66         3738.28
Permanent Ineff=
       F       F
Bank Sta=335.37,353.5
XS Rating Curve= 0 ,0
Exp/Cntr(USF)=0,0
Exp/Cntr=0.3,0.1

Type RM Length L Ch R = 1 ,7388    ,293.7,293.4,286.7
XS GIS Cut Line= 3
 2278258.3011357586241.9048427922278196.51779703585918.326436842
2278086.72851076585362.782575286
#Sta/Elev= 30
       0 3783.59    25.2 3781.02    94.4 3770.76     105 3768.01   118.8 3767.55
   143.3 3761.43   156.3 3755.95   192.1 3743.93   212.5 3741.26   249.1 3739.31
   257.3 3735.83   265.4 3730.32   272.6 3727.88   285.8 3725.44   289.9 3725.81
  294.18 3727.88     298 3729.42   314.3 3730.83   375.4 3730.42   416.2 3737.76
   444.8 3738.47   505.9    3737   522.2 3738.83   538.5 3738.07   624.2 3742.91
   722.2 3746.29   754.6  3748.9   787.8 3748.19   868.8 3754.76   895.7  3759.5
#Mann= 8 ,-1,0
       0      .1       0      10     .12       0     210      .1       0
   272.6    .045       0  294.18      .1       0  419.42     .12       0
  519.42      .1       0  719.42     .12       0
Bank Sta=272.6,294.18
XS Rating Curve= 0 ,0
Exp/Cntr=0.3,0.1

Type RM Length L Ch R = 1 ,7095    ,345.9,344.6,338.8
XS GIS Cut Line= 4
2278490.67709395586191.2584264452278503.98325878585981.021022043
2278267.13352471585505.9909374142278245.84366097585356.961891255
#Sta/Elev= 30
       0 3780.28   102.3 3759.17   114.3  3755.2   142.8 3741.94   158.4 3739.33
   198.5 3736.63   210.7 3731.63   228.4 3728.68   246.1 3728.29   261.1 3725.35
   281.9 3726.28   304.3 3725.06   326.6 3728.06   366.9 3725.95   389.3  3727.5
   402.7 3726.35   420.6 3727.27   432.33723.881   440.1 3722.78     452 3723.92
   487.6 3727.08   505.5 3732.27   532.3 3735.22   563.6 3735.14   595.1 3738.35
   702.1 3742.06   778.6 3748.34   802.9 3748.88   863.5 3756.32     892 3756.73
#Mann= 11 ,-1,0
       0     .12       0     160      .1       0  240.66     .12       0
  260.66      .1       0  370.66     .12       0   432.3    .045       0
     452     .12       0  480.66      .1       0  590.66     .12       0
  680.66      .1       0  700.66     .12       0
#XS Ineff= 2 , 0
           393.5 3732.67
Permanent Ineff=
       F       F
Bank Sta=432.3,452
XS Rating Curve= 0 ,0
Exp/Cntr(USF)=0,0
Exp/Cntr=0.3,0.1

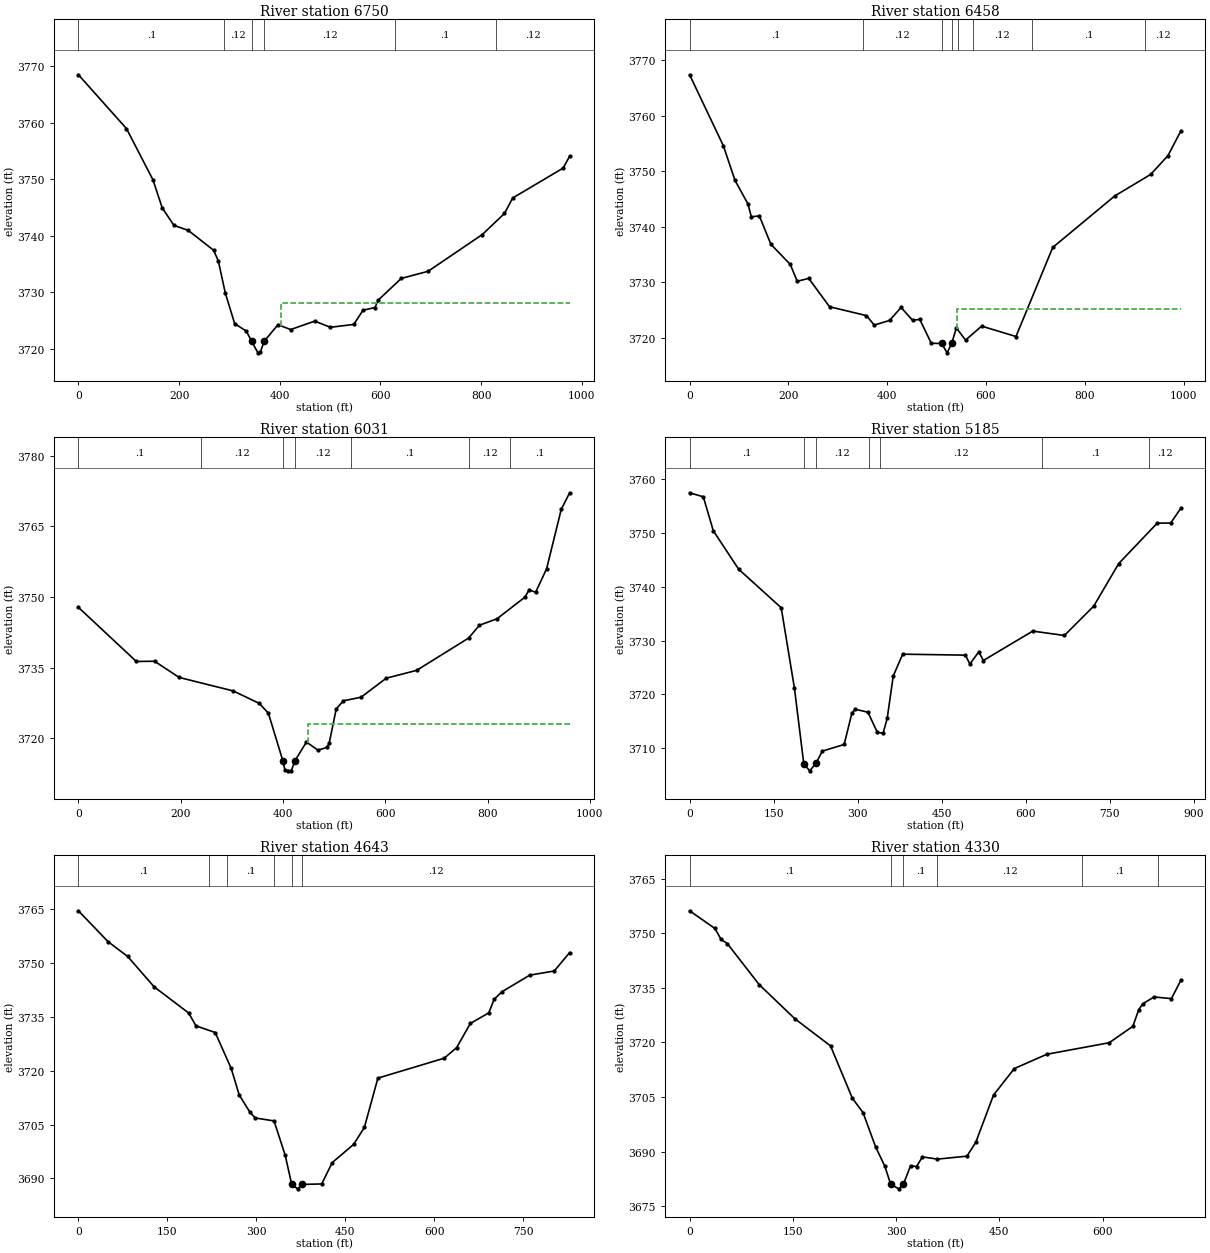
Type RM Length L Ch R = 1 ,6750    ,288.7,292.7,285.9
BEGIN DESCRIPTION:
Area disconnected without IFA
END DESCRIPTION:
XS GIS Cut Line= 3
2278859.25082517 586180.767427462278545.72246773585647.126544394
2278466.92225538585298.814138444
#Sta/Elev= 30
       0 3768.52    95.5    3759   148.1 3749.93   166.5 3744.97   189.7 3741.87
   218.2 3740.98   268.6 3737.46   277.9  3735.6   291.8  3729.9   310.4 3724.49
   333.6 3723.15   343.9 3721.39   356.7 3719.31   361.4 3719.44  369.133721.357
   396.5 3724.29   421.7 3723.43   469.5 3724.92   500.6 3723.83     547 3724.34
   565.5 3726.85   589.3 3727.33   595.2  3728.6   641.4 3732.48   694.7 3733.74
   802.5 3740.25   846.5 3743.98   862.9 3746.72     963    3752     976 3754.11
#Mann= 6 ,-1,0
       0      .1       0     290     .12       0   343.9    .045       0
  369.13     .12       0  628.93      .1       0  828.93     .12       0
#XS Ineff= 2 , 0
                          402.89          3728.1
Permanent Ineff=
       F       F
Bank Sta=343.9,369.13
XS Rating Curve= 0 ,0
Exp/Cntr=0.3,0.1

Type RM Length L Ch R = 1 ,6458    ,425.5,426.7,414.1
XS GIS Cut Line= 3
     2279065.024      586131.749     2278795.394      585683.996
     2278555.615      585277.864
#Sta/Elev= 30
       0 3767.33    68.4 3754.54    91.7 3748.36     118  3744.1   124.9 3741.78
   141.2 3741.92   164.5 3736.82   203.8 3733.19   217.8 3730.16   241.1 3730.68
   283.2 3725.58   357.9 3723.98   373.8 3722.28   404.7 3723.11     428 3725.45
   451.2 3723.15   465.9 3723.29   489.2    3719  510.213718.964   521.2 3717.28
   530.6 3719.01   539.9 3721.77   558.5 3719.57     591 3722.09   660.6 3720.22
     735 3736.25   860.4 3745.51   933.1 3749.39   968.1 3752.76   994.3 3757.22
#Mann= 8 ,-1,0
       0      .1       0     350     .12       0  510.21    .045       0
   530.6     .12       0  542.67      .1       0  572.67     .12       0
  692.67      .1       0  922.67     .12       0
#XS Ineff= 2 , 0
                          541.52         3725.21
Permanent Ineff=
       F       F
Bank Sta=510.21,530.6
XS Rating Curve= 0 ,0
Exp/Cntr=0.3,0.1

Type RM Length L Ch R = 1 ,6031    ,829,846,842.6
XS GIS Cut Line= 4
2279266.96803089585951.9571720832279118.91541261585631.156789118
2278962.34093822585541.487744622     2278821.935      585138.621
#Sta/Elev= 30
       0 3747.79   113.2 3736.29   148.9 3736.34   196.9  3732.9   302.7 3730.03
   353.8 3727.37   371.4  3725.3  399.863715.118   403.7 3713.23   409.5 3713.05
   416.4  3713.1  422.643715.065   445.8 3719.18   468.2 3717.44   485.5 3718.01
   490.2 3718.89     504  3726.2     518 3727.93   552.5 3728.69   601.9 3732.74
   661.2  3734.4   762.8 3741.26     784 3743.99   818.4 3745.37     873 3749.96
   881.2 3751.53   893.8 3750.98   915.3 3755.98     944 3768.63   960.4 3772.14
#Mann= 7 ,-1,0
       0      .1       0     240     .12       0  399.86    .045       0
  422.64     .12       0  533.32      .1       0  763.75     .12       0
  843.75      .1       0
#XS Ineff= 2 , 0
                          448.38         3723.03
Permanent Ineff=
       F       F
Bank Sta=399.86,422.64
XS Rating Curve= 0 ,0
Exp/Cntr=0.3,0.1

Type RM Length L Ch R = 1 ,5185    ,539.6,542,538.3
XS GIS Cut Line= 4
2279535.84233478585826.6394986272279362.35587368585499.002775515
2279359.02446227585279.9228900342279318.20812906 584995.30426476
#Sta/Elev= 30
       0  3757.5    24.5 3756.75    42.3 3750.44    87.6 3743.28   163.6 3736.12
   187.3 3721.11   203.93707.121   214.4 3705.78   225.6 3707.16     237 3709.45
     276 3710.68   289.9 3716.54   295.9 3717.24   318.5 3716.68   335.2 3712.96
   345.6 3712.75     353 3715.59   363.7 3723.42   380.6 3727.48   492.6  3727.3
   500.6 3725.64   516.5 3727.92   524.6  3726.3   612.8 3731.77   669.4 3730.96
   721.9 3736.43   766.4 3744.33   835.1 3751.84   859.3 3751.88   877.4 3754.63
#Mann= 7 ,-1,0
       0      .1       0   203.9    .045       0   225.6     .12       0
     320      .1       0     340     .12       0  629.84      .1       0
  819.84     .12       0
Bank Sta=203.9,225.6
XS Rating Curve= 0 ,0
Exp/Cntr=0.3,0.1

Type RM Length L Ch R = 1 ,4643    ,310.4,312.5,312.2
XS GIS Cut Line= 3
2279881.72679977585639.1001599542279677.85500275585236.428095423
2279496.61769497584905.493083295
#Sta/Elev= 30
       0  3764.5    50.2 3755.87    83.1 3751.78   127.7 3743.34     186 3736.04
   198.3 3732.48   230.8  3730.6   257.7 3720.63   271.2 3713.24   289.1 3708.49
   298.1 3706.83     330 3706.01   348.8 3696.46   359.8 3688.33   369.8  3687.1
   377.6 3688.33   410.4 3688.46   428.2 3694.41   464.2 3699.46   482.4 3704.19
   505.2 3717.92     617 3723.46     638  3726.4   661.2 3733.14   692.2 3736.08
   701.3 3739.85   714.3 3741.94   761.4 3746.58   802.7 3747.74   828.7 3752.87
#Mann= 6 ,-1,0
       0      .1       0     220     .12       0     250      .1       0
     330     .12       0   359.8    .045       0   377.6     .12       0
Bank Sta=359.8,377.6
XS Rating Curve= 0 ,0
Exp/Cntr=0.3,0.1

Type RM Length L Ch R = 1 ,4330    ,224.9,225.2,225.6
XS GIS Cut Line= 2
2280101.13600934585483.3955944162279837.12709731 584820.37876287
#Sta/Elev= 30
       0 3756.18    36.8 3751.31    45.8 3748.29    54.8 3747.16     101  3735.9
   153.1 3726.47   204.7 3719.05   236.5 3704.63   251.9 3700.72   270.3 3691.24
   283.7 3685.93292.07623681.013   303.8 3679.76  310.59 3681.02     321 3686.11
   329.6 3685.88   338.2 3688.54     360 3687.93   402.9 3688.74   415.7 3692.54
   441.5 3705.55   471.7 3712.82     519 3716.75   609.5 3719.91   643.9 3724.43
   652.5 3729.04   658.3 3730.62   674.7 3732.49   699.9 3732.04   713.6 3737.08
#Mann= 6 ,-1,0
       0      .1       0292.0762    .045       0  310.59      .1       0
     360     .12       0     570      .1       0     680     .12       0
Bank Sta=292.0762,310.59
XS Rating Curve= 0 ,0
Exp/Cntr(USF)=0,0
Exp/Cntr=0.3,0.1

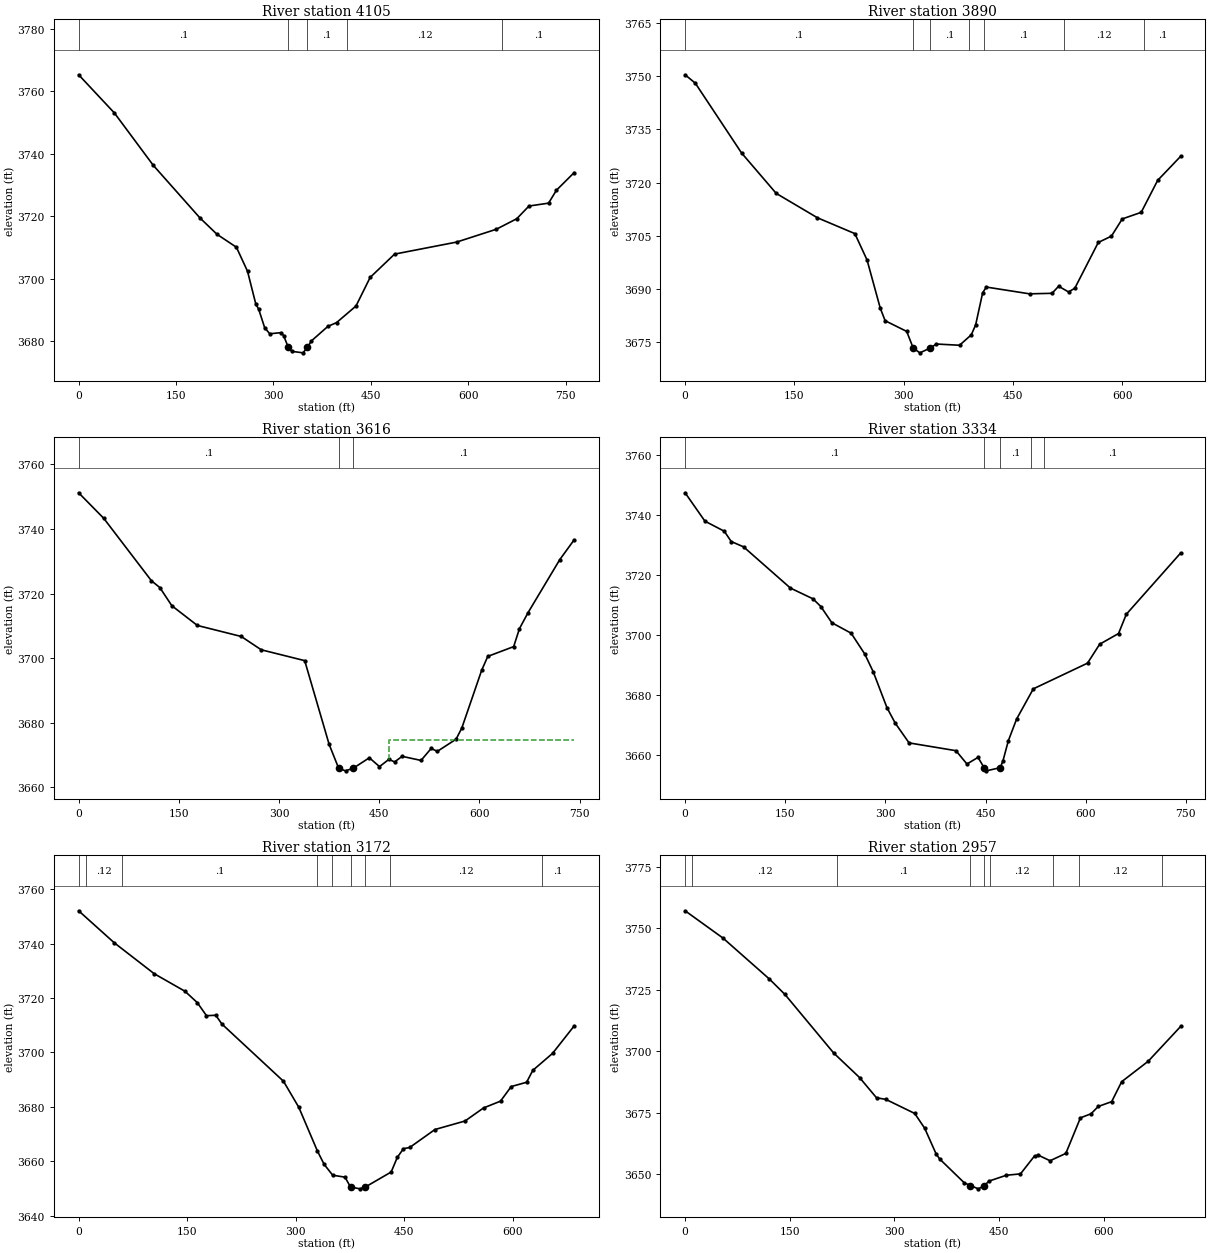
Type RM Length L Ch R = 1 ,4105    ,217.1,215.4,213.3
XS GIS Cut Line= 3
2280317.00448199585436.8132660632280179.83567681585069.075713949
2279985.11484615 584754.02337253
#Sta/Elev= 30
       0 3765.34    55.1 3753.09   114.9 3736.32   186.9 3719.43   213.1  3714.2
   242.9 3710.07     260 3702.37   272.8 3691.83   277.1 3690.26   286.4 3684.28
   294.2 3682.33   311.3 3682.69   315.5 3681.76   322.8    3678   328.3  3676.7
   345.4 3676.22   352.3 3677.96   358.2 3680.01   383.8 3684.71   397.1 3685.91
     427 3691.23   448.8 3700.39   486.4 3707.86     582 3711.72   642.9 3715.82
   674.5  3719.2   693.3 3723.27   723.5  3724.2   735.6 3728.34   762.9 3733.99
#Mann= 5 ,-1,0
       0      .1       0   322.8    .045       0   352.3      .1       0
  412.49     .12       0  652.49      .1       0
Bank Sta=322.8,352.3
XS Rating Curve= 0 ,0
Exp/Cntr=0.3,0.1

Type RM Length L Ch R = 1 ,3890    ,274.2,273.5,267.1
XS GIS Cut Line= 2
 2280542.9021445585309.5295055862280223.55418844584709.421471503
#Sta/Elev= 30
       0 3750.43      14 3748.06    77.4 3728.37     125 3716.94   181.6 3710.05
   232.9 3705.58   249.6 3698.14   267.7 3684.56   274.4 3680.99     304 3677.97
     313 3673.23   322.1 3671.92  335.97 3673.25   344.8 3674.41   376.5 3674.06
   392.6    3677   398.6 3679.82   408.2 3688.88   413.3 3690.49   472.5 3688.58
   503.4 3688.73   512.4 3690.72     526 3689.12   534.6 3690.15   566.8 3703.08
   584.9 3704.88   599.7 3709.73   625.7 3711.59   648.3 3720.62   679.8  3727.4
#Mann= 7 ,-1,0
       0      .1       0     313    .045       0  335.97      .1       0
     390     .12       0     410      .1       0     520     .12       0
     630      .1       0
Bank Sta=313,335.97
XS Rating Curve= 0 ,0
Exp/Cntr(USF)=0,0
Exp/Cntr=0.3,0.1

Type RM Length L Ch R = 1 ,3616    ,275.9,282,288.1
XS GIS Cut Line= 4
2280744.20558457585252.9392039912280638.70653131584926.311958322
2280482.28290048584769.7713620072280415.92641301584605.184761944
#Sta/Elev= 30
       0  3751.2    37.6 3743.29     109 3723.96   121.6 3721.85   139.6 3716.22
   177.8 3710.12   243.5 3706.71   273.4 3702.59   338.5 3699.23   375.1  3673.3
  389.373665.906   399.6 3665.11   410.9 3665.88   435.3 3669.15   450.5 3666.42
   464.6 3668.66   473.1 3667.87   484.4  3669.6   512.7 3668.33   527.9 3672.05
   537.1 3671.14   565.2 3674.91   573.8 3678.39   603.5 3696.25   612.6 3700.54
   651.4 3703.57   660.1 3709.15     673 3714.11   720.4 3730.49     742 3736.64
#Mann= 3 ,-1,0
       0      .1       0  389.37    .045       0   410.9      .1       0
#XS Ineff= 2 , 0
                          464.08         3674.73
Permanent Ineff=
       F       F
Bank Sta=389.37,410.9
XS Rating Curve= 0 ,0
Exp/Cntr=0.3,0.1

Type RM Length L Ch R = 1 ,3334    ,163.5,162.7,162.2
XS GIS Cut Line= 3
2280895.53617732585157.9682701112280765.94443092584656.829984313
2280646.88209224584466.330242437
#Sta/Elev= 30
       0 3747.47    29.7 3737.99    58.7 3734.63    69.1 3731.19    87.6 3729.41
   157.8 3715.64   191.5 3712.06   203.3 3709.49   219.8 3704.07   248.7 3700.58
   269.1 3693.64   281.8 3687.69   302.4  3675.7   314.8 3670.53   335.5 3663.94
   405.7 3661.34   422.2  3656.9   438.8  3659.1   447.8  3655.7   451.2 3654.61
471.94223655.667   476.1  3657.9   484.2 3664.66   496.6 3671.91   521.6 3681.99
   602.8 3690.57     621 3696.89   649.3 3700.47   660.9 3706.89   742.3 3727.35
#Mann= 5 ,-1,0
       0      .1       0   447.8    .045       0471.9422      .1       0
  517.62     .12       0  537.62      .1       0
Bank Sta=447.8,471.9422
XS Rating Curve= 0 ,0
Exp/Cntr(USF)=0,0
Exp/Cntr=0.3,0.1

Type RM Length L Ch R = 1 ,3172    ,217.7,214.8,211.3
XS GIS Cut Line= 2
2281072.48750495585059.3736066782280839.62962033584415.355228637
#Sta/Elev= 30
       0 3752.02    49.1 3740.29   104.4 3728.91     147 3722.45     164 3718.28
   176.7 3713.48   189.5 3713.64     198 3710.41   283.1  3689.4   304.3 3679.81
     330 3663.76   339.3 3658.86   351.1 3654.89   368.1 3654.17  375.713650.541
   389.1 3649.88   396.2 3650.55   431.9 3656.06   440.4 3661.45   448.9 3664.63
   457.5 3665.07   492.4 3671.67     534  3674.8   559.5 3679.59     583 3682.09
   597.8 3687.45   619.1 3689.03   627.6 3693.39   654.9 3699.63   684.8 3709.72
#Mann= 9 ,-1,0
       0      .1       0      10     .12       0      60      .1       0
     330     .12       0     350      .1       0  375.71    .045       0
   396.2      .1       0     430     .12       0     640      .1       0
Bank Sta=375.71,396.2
XS Rating Curve= 0 ,0
Exp/Cntr(USF)=0,0
Exp/Cntr=0.3,0.1

Type RM Length L Ch R = 1 ,2957    ,260.3,261.1,262.4
XS GIS Cut Line= 5
2281259.78025502584957.353588951 2281246.7982643584911.675177003
2281168.77201009584642.9393781352281037.34710755584470.992267506
2280933.85587094584340.806827918
#Sta/Elev= 30
       0 3757.08    54.3 3745.98   120.9  3729.3     143 3723.09     213 3699.22
     250 3689.27   274.3 3681.04   287.5 3680.41     329 3674.68   343.3 3668.67
   359.7 3658.22   364.8 3656.16     400 3646.48408.9018 3645.36   420.2 3644.02
428.90193645.331   435.3 3647.15   460.4 3649.55   480.6  3650.1   500.7 3657.38
   506.2  3657.7     523 3655.44   545.6 3658.43   566.5 3672.88   581.8 3674.56
     592  3677.5   611.3 3679.48   625.6 3687.58   663.6 3695.89   710.1 3710.04
#Mann= 9 ,-1,0
       0      .1       0      10     .12       0  217.49      .1       0
408.9018    .045       0428.9019      .1       0  437.32     .12       0
  527.32      .1       0  563.74     .12       0  683.74      .1       0
Bank Sta=408.9018,428.9019
XS Rating Curve= 0 ,0
Exp/Cntr=0.3,0.1