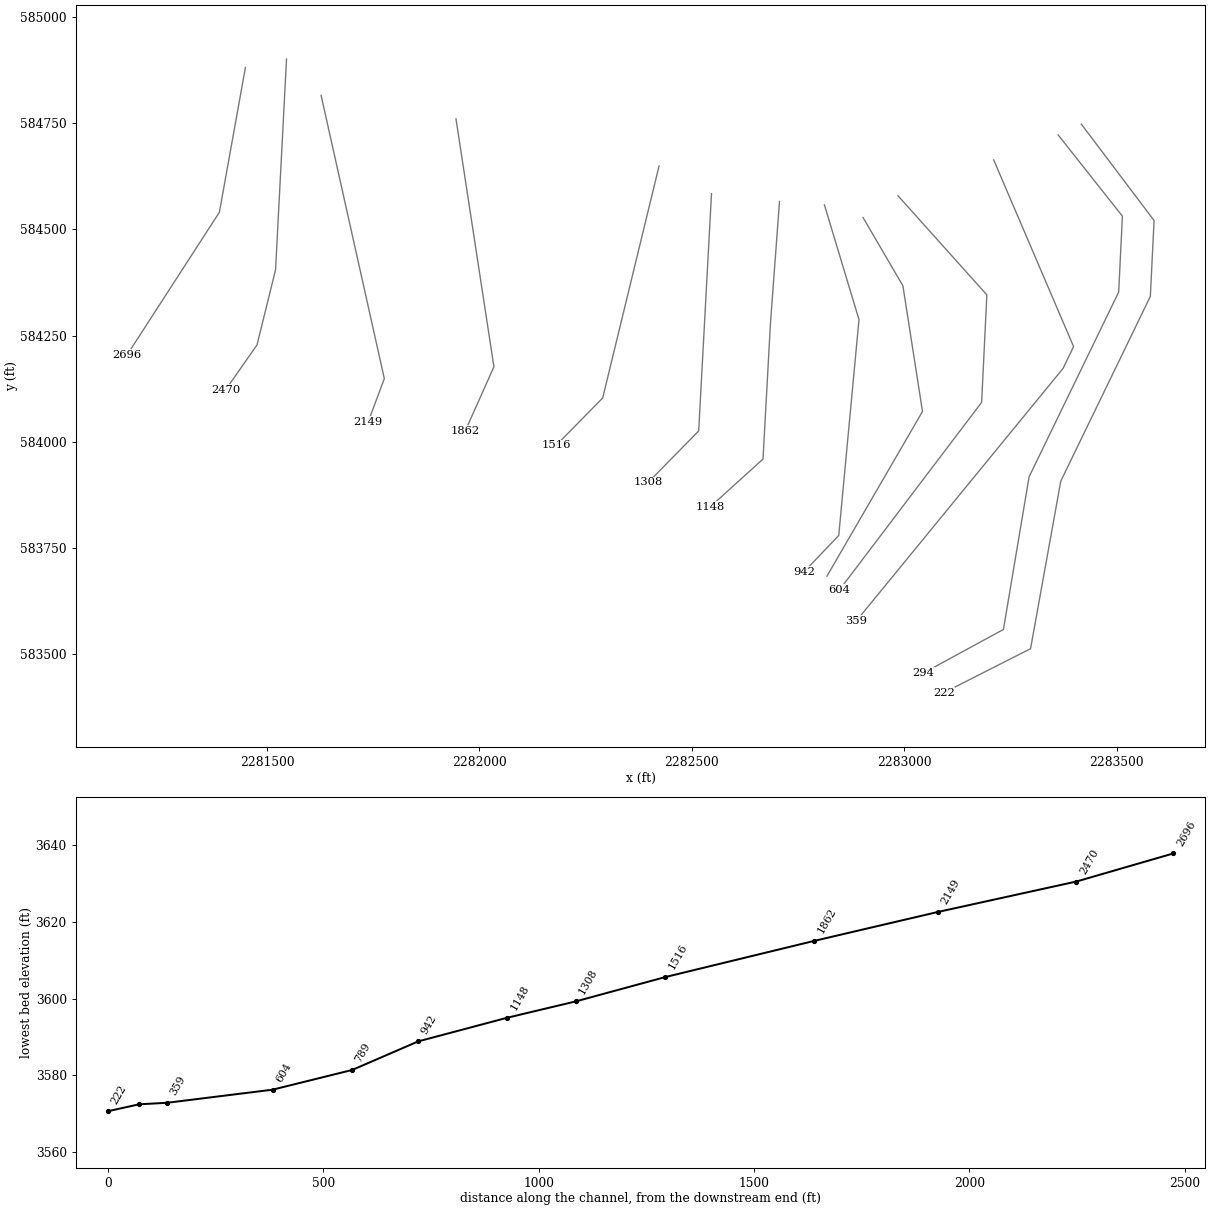
HEC-RAS study LAMBERTRN.prj: LAMBERTRN

--- LAMBERTRN.g01 (geometry) --- (continued)

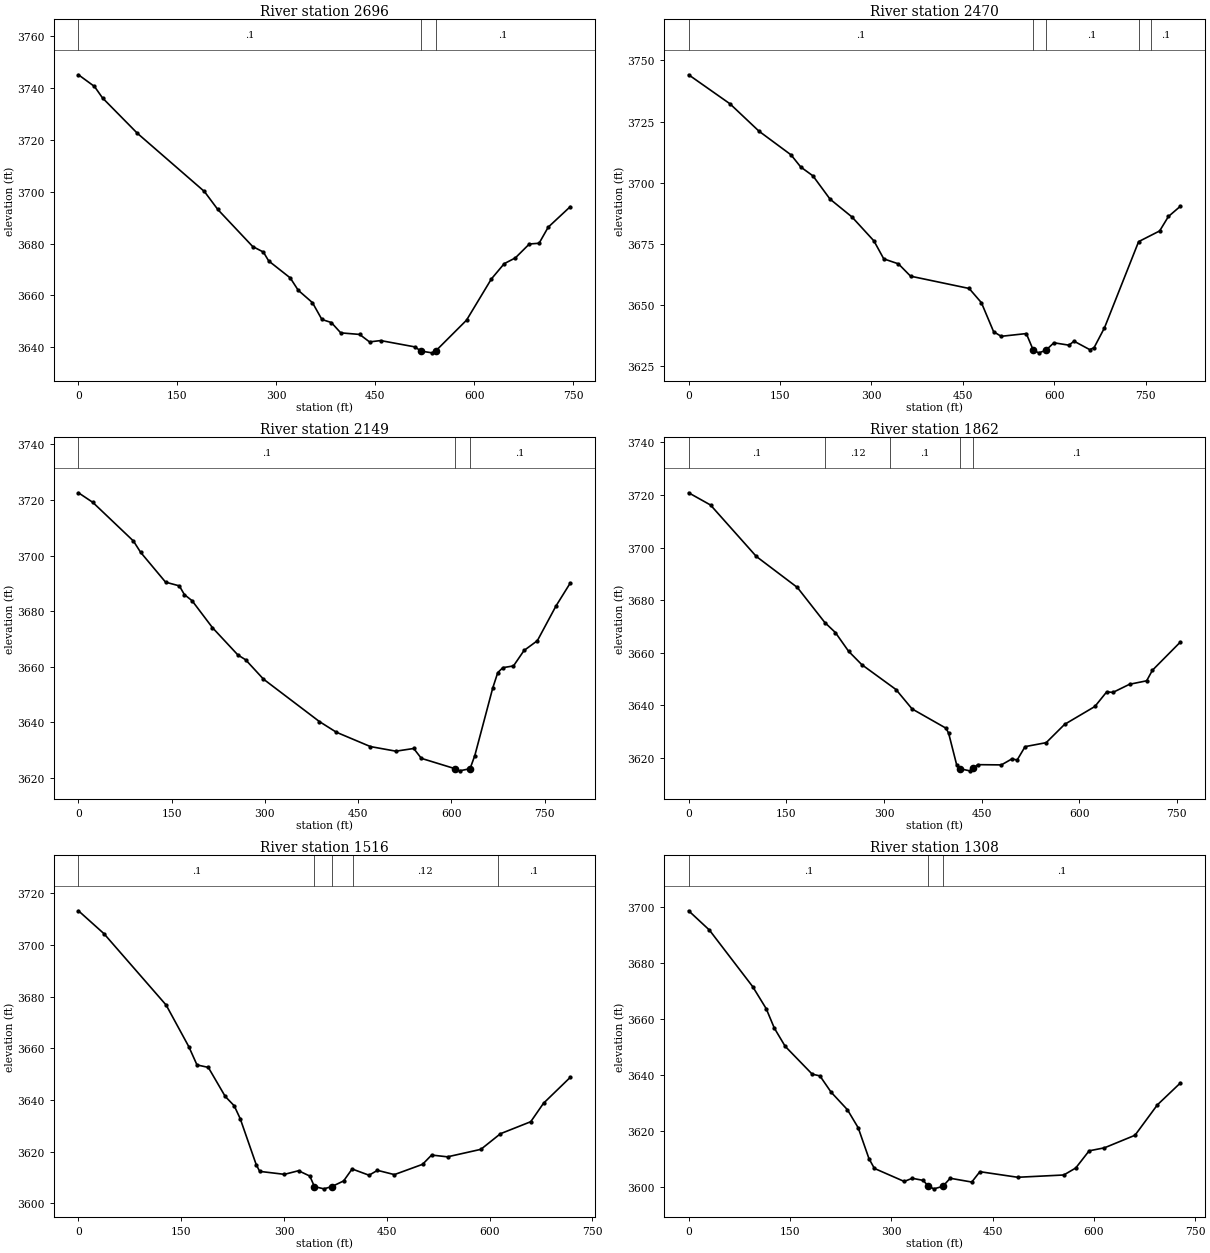
Type RM Length L Ch R = 1 ,2696    ,222.5,225.3,229.7
XS GIS Cut Line= 3
 2281449.0519698584881.0709978812281387.84361155584540.433178091
2281170.95312473584205.117824235
#Sta/Elev= 30
       0 3745.09    24.3 3740.58    36.5 3736.16    89.3 3722.53   190.9 3700.08
   211.2 3693.15   264.1 3678.86   280.3 3676.73   288.4 3673.29     321 3666.76
   333.1    3662   354.7 3657.21     369 3650.73   383.3 3649.55   397.6 3645.56
   426.2 3644.96   441.2 3642.08   458.1 3642.59   510.2 3640.14   518.9 3638.55
   535.8 3637.86  541.333638.537   588.2 3650.45   625.9 3666.36   645.3 3672.24
   662.2 3674.47   683.4 3679.83   698.2 3680.12     712 3686.31   745.4 3694.22
#Mann= 3 ,-1,0
       0      .1       0   518.9    .045       0  541.33      .1       0
Bank Sta=518.9,541.33
XS Rating Curve= 0 ,0
Exp/Cntr(USF)=0,0
Exp/Cntr=0.3,0.1

Type RM Length L Ch R = 1 ,2470    ,310.8,321.9,324
XS GIS Cut Line= 4
2281545.80274922584900.9077785922281520.00590918584404.814700789
2281476.34971833584228.2055650912281402.92794281584123.033832597
#Sta/Elev= 30
       0  3744.1    67.8 3732.25   115.5 3721.05     168 3711.39     184 3706.42
     204 3702.81     232 3693.32   268.1 3686.01   304.1 3676.23   320.2 3668.91
   344.2 3666.88   364.2 3661.84   460.3 3656.82   480.4 3651.02   500.5 3639.13
   512.9 3637.28   554.1  3638.4   565.7 3631.53   574.7 3630.53  586.033631.549
   599.4 3634.64   624.1 3633.66   632.4 3635.29   658.2 3631.84   665.3 3632.65
   682.4 3640.77   738.4 3675.95   772.9 3680.32   787.3 3686.22     807 3690.42
#Mann= 5 ,-1,0
       0      .1       0   565.7    .045       0  586.03      .1       0
  738.69     .12       0  758.69      .1       0
Bank Sta=565.7,586.03
XS Rating Curve= 0 ,0
Exp/Cntr(USF)=0,0
Exp/Cntr=0.3,0.1

Type RM Length L Ch R = 1 ,2149    ,283.4,286.6,283.4
XS GIS Cut Line= 3
2281627.16201398 584815.579769212281775.98993732584148.830672643
2281738.28686341584047.627684771
#Sta/Elev= 30
       0 3722.59      23 3719.16    88.5 3705.23     100 3701.19   140.2 3690.44
   162.3 3689.11   170.5 3685.95   182.8 3683.78   215.6 3674.08   256.6 3664.24
   268.9 3662.54   297.7 3655.56   387.7  3640.3     415 3636.46   469.7 3631.31
   510.7 3629.65   539.4 3630.62   551.7 3627.07  605.293623.391   613.1 3622.58
  630.033623.354   637.7 3628.08   666.6 3652.42   674.6  3657.9   682.8 3659.69
   699.9 3660.31   716.9 3665.87   738.3 3669.38   768.2 3681.84   791.2 3690.11
#Mann= 3 ,-1,0
       0      .1       0  605.29    .045       0  630.03      .1       0
Bank Sta=605.29,630.03
XS Rating Curve= 0 ,0
Exp/Cntr(USF)=0,0
Exp/Cntr=0.3,0.1

Type RM Length L Ch R = 1 ,1862    ,348.1,345.6,339.1
XS GIS Cut Line= 3
2281944.66158378584760.0173444962282033.95833778   584176.611885
 2281966.4896792584025.799589348
#Sta/Elev= 30
       0 3720.83    33.6 3716.18     104  3696.6     167 3684.81   209.2 3671.47
   225.4 3667.67   245.7 3660.54   265.9 3655.46   318.5 3645.98   343.2 3638.61
   395.4 3631.26   399.4 3629.32   411.6 3617.42   416.2 3615.88   431.8 3615.05
     4373615.944   443.9  3617.4   480.4 3617.31   496.6  3619.6   504.6 3619.17
   516.8 3624.26   549.2 3625.77   577.5 3632.73     624 3639.53   642.2 3645.11
   651.7 3644.88   677.2 3647.98   703.5  3649.3   712.4 3653.32   755.4 3664.07
#Mann= 5 ,-1,0
       0      .1       0     210     .12       0     310      .1       0
   416.2    .045       0     437      .1       0
Bank Sta=416.2,437
XS Rating Curve= 0 ,0
Exp/Cntr(USF)=0,0
Exp/Cntr=0.3,0.1

Type RM Length L Ch R = 1 ,1516    ,206.1,208.7,209.1
XS GIS Cut Line= 3
 2282422.6338366584649.2853888512282289.94236593584103.190109485
2282180.80188881583992.065260057
#Sta/Elev= 30
       0 3713.26    37.2 3704.41     128 3676.76   161.1 3660.64     173 3653.59
   189.5 3652.64   214.2 3641.39   227.3 3637.78   236.1 3632.77   259.4 3615.01
   264.5 3612.38   300.6 3611.23   321.2 3612.63   337.7 3610.56  344.353606.496
   358.2 3605.62369.73793606.495     387 3608.68   399.4 3613.31   424.1 3610.89
   436.4 3612.78   461.1 3611.13   502.2 3615.11   515.4  3618.7   538.6 3618.01
   587.3 3620.91   615.9 3626.96   660.1 3631.61   678.7 3638.75   717.7 3648.77
#Mann= 5 ,-1,0
       0      .1       0  344.35    .045       0369.7379      .1       0
     400     .12       0  611.98      .1       0
Bank Sta=344.35,369.7379
XS Rating Curve= 0 ,0
Exp/Cntr(USF)=0,0
Exp/Cntr=0.3,0.1

Type RM Length L Ch R = 1 ,1308    ,158.3,159.4,158.7
XS GIS Cut Line= 3
2282546.05714667584583.8865250072282515.87876482584025.586460837
2282397.32083614583904.872933449
#Sta/Elev= 30
       0 3698.81    30.8 3691.89    94.8 3671.67   114.9 3663.74   126.9  3656.8
   142.9  3650.3     183 3640.31   194.4 3639.69     211 3633.86   235.1 3627.59
   251.1 3621.12   267.1 3610.04   275.1 3606.56   319.2  3601.9   331.2 3603.03
   347.2 3602.28   355.2 3600.17   363.2 3599.25  376.443600.138   387.3 3603.04
   419.3 3601.68   431.3 3605.39   487.4 3603.39   555.6 3604.21   573.3 3606.72
   593.1 3612.86   615.8 3613.94     661 3618.43   694.2 3629.33   728.3 3637.17
#Mann= 3 ,-1,0
       0      .1       0   355.2    .045       0  376.44      .1       0
Bank Sta=355.2,376.44
XS Rating Curve= 0 ,0
Exp/Cntr(USF)=0,0
Exp/Cntr=0.3,0.1

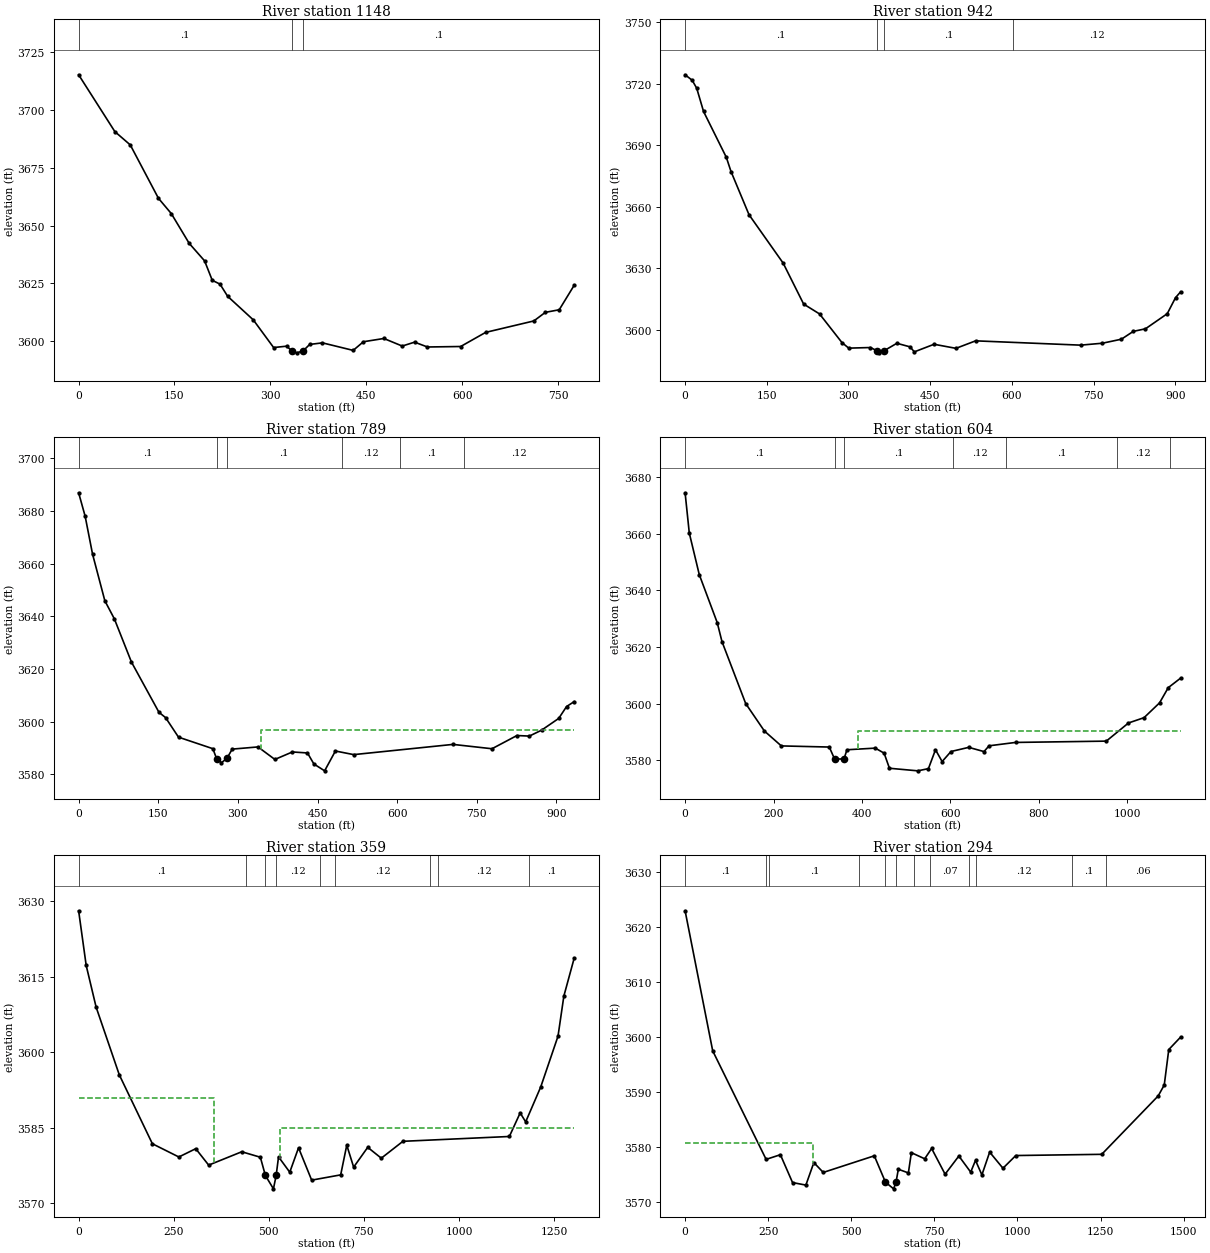
Type RM Length L Ch R = 1 ,1148    ,206.2,206,205.5
XS GIS Cut Line= 4
 2282706.1163345584565.7506219922282684.90280025 584280.53459175
2282667.25448263583959.3781925152282542.83368481583846.813187556
#Sta/Elev= 30
       0 3715.27    56.7 3690.68    80.8 3684.93   124.9 3661.83     145 3655.22
     173 3642.34   197.1 3634.77   209.1 3626.35   221.2 3624.71   233.2 3619.43
   273.3 3609.24   305.1 3597.27   325.4 3597.86333.77263595.824   341.4 3594.98
  351.223595.813   361.5 3598.61   381.5  3599.3   429.6 3596.04   445.6 3599.78
   477.6 3601.19   506.3 3597.92   525.7  3599.6   545.8 3597.51   597.8 3597.72
   636.9 3603.83   712.3 3608.78   730.3  3612.5     752 3613.61   775.4  3624.2
#Mann= 3 ,-1,0
       0      .1       0333.7726    .045       0  351.22      .1       0
Bank Sta=333.7726,351.22
XS Rating Curve= 0 ,0
Exp/Cntr(USF)=0,0
Exp/Cntr=0.3,0.1

Type RM Length L Ch R = 1 ,942     ,152.5,153.5,153.2
XS GIS Cut Line= 4
2282811.83228377584557.6113687522282893.19154853584287.736734428
2282845.56661307583779.7374227572282764.20734831583694.409413375
#Sta/Elev= 30
       0 3724.42      13 3721.75    21.3 3717.88    33.9 3706.52    75.7 3684.17
    84.3 3677.25   117.4 3656.17   180.1 3632.57   217.7 3612.61   246.9  3607.8
     288 3593.85   300.5 3591.12   340.3 3591.42   351.83589.928   356.8 3588.83
     366 3589.95   388.9 3593.49     413 3591.75     421 3589.31   457.2 3593.01
   497.4 3591.02   533.5 3594.68   726.4 3592.58   766.3 3593.52   801.2 3595.48
   823.1  3599.3   845.4 3600.55   885.4 3607.91   900.6 3615.73     910  3618.6
#Mann= 4 ,-1,0
       0      .1       0   351.8    .045       0     366      .1       0
  601.87     .12       0
Bank Sta=351.8,366
XS Rating Curve= 0 ,0
Exp/Cntr(USF)=0,0
Exp/Cntr=0.3,0.1

Type RM Length L Ch R = 1 ,789     ,187.4,184.8,183.1
XS GIS Cut Line= 4
2282902.80873207 584527.840958722282996.57727567 584367.24885532
2283042.64478583584071.4617422372282817.82357146583683.949364495
#Sta/Elev= 30
       0 3686.97    12.3 3678.04    26.2 3663.68    49.4 3645.94    67.3 3639.09
    99.5 3622.67   151.3  3603.6   163.8 3601.57   188.1 3594.16   252.8 3589.78
  259.77 3586.04     269 3584.47   279.13586.058   289.3 3589.62   337.8 3590.45
   369.6  3585.7   402.6 3588.54     431 3588.16   443.1 3583.97   463.3 3581.37
   483.6  3588.9   518.1 3587.53   705.1 3591.41   778.5 3589.76   825.5 3594.78
   848.9 3594.57   871.8  3596.8   904.2 3601.28     919  3605.8   933.3 3607.65
#Mann= 6 ,-1,0
       0      .1       0  259.77    .045       0   279.1      .1       0
  495.32     .12       0  605.32      .1       0  725.32     .12       0
#XS Ineff= 2 , 0
                           344.4         3596.97
Permanent Ineff=
       F       F
Bank Sta=259.77,279.1
XS Rating Curve= 0 ,0
Exp/Cntr(USF)=0,0
Exp/Cntr=0.3,0.1

Type RM Length L Ch R = 1 ,604     ,248.8,245.3,241.7
XS GIS Cut Line= 4
2282984.90760484584579.2896557412283194.15013351584345.896772244
2283181.84119754584092.8950074962282846.91774728 583651.14359005
#Sta/Elev= 30
       0  3674.4     9.5 3660.16    32.1 3645.49    72.7 3628.55    83.4 3621.88
   137.1 3599.98   179.4 3590.29   217.7 3585.03   326.2 3584.63   338.2  3580.4
  359.47 3580.42   366.2 3583.67   430.3 3584.25   450.3 3582.46   462.3 3577.14
   526.4 3576.23   550.5 3577.01   566.5 3583.68   581.5  3579.5   601.5 3583.05
   641.7 3584.52   676.2 3583.03   687.7 3585.07   747.6 3586.26   952.9 3586.72
  1003.1 3593.13  1038.3    3595  1073.4 3600.23  1093.1  3605.6  1121.1 3608.97
#Mann= 7 ,-1,0
       0      .1       0   338.2    .045       0  359.47      .1       0
  606.76     .12       0  726.76      .1       0  976.76     .12       0
 1096.76      .1       0
#XS Ineff= 2 , 0
                          391.79         3590.16
Permanent Ineff=
       F       F
Bank Sta=338.2,359.47
XS Rating Curve= 0 ,0
Exp/Cntr(USF)=0,0
Exp/Cntr=0.3,0.1

Type RM Length L Ch R = 1 ,359     ,64.6,64.5,64.5
BEGIN DESCRIPTION:
Structure XS 4
END DESCRIPTION:
XS GIS Cut Line= 4
2283210.26185645 584663.466373072283398.26772119584224.175094308
2283373.56262709584172.8927005322282886.99884178583578.530501413
#Sta/Elev= 30
       0 3628.15    19.9 3617.26      46 3608.97   106.9  3595.5   193.9 3581.78
   263.5 3579.15   307.9  3580.8   341.9 3577.53   428.9 3580.19   477.8  3579.1
     4913575.473   512.2 3572.81  519.35 3575.47   525.6 3579.18   555.1 3576.12
   578.2 3580.98   612.7 3574.54     689 3575.59     705  3581.5   723.1 3577.13
   760.1 3581.07   795.8 3578.91   852.7 3582.27  1132.5 3583.23  1160.9 3587.92
  1175.4 3586.14  1214.9 3593.07  1260.4 3603.19  1275.8 3611.18  1302.9 3618.71
#Mann= 9 ,-1,0
       0      .1       0     440     .12       0     491    .045       0
  519.35     .12       0  634.75      .1       0  674.75     .12       0
  924.75      .1       0  944.75     .12       0 1184.75      .1       0
#XS Ineff= 2 , 0
          355.64 3590.81  529.12         3584.87
Permanent Ineff=
       F       F
Bank Sta=491,519.35
XS Rating Curve= 0 ,0
Exp/Cntr(USF)=0,0
Exp/Cntr=0.3,0.1

Type RM Length L Ch R = 1 ,294     ,72.6,72.5,71.8
BEGIN DESCRIPTION:
Structure XS 3
END DESCRIPTION:
XS GIS Cut Line= 6
2283361.94811525584722.3369759952283513.17835612584531.087810056
 2283504.3929302584352.450816417 2283293.5427082583917.572233544
2283233.15272637583558.3857478432283044.86258904583455.922703146
#Sta/Elev= 30
       0 3622.93    83.1 3597.48   243.8 3577.77   286.7 3578.62   323.3 3573.56
   363.4  3573.1   387.4 3577.19   415.7  3575.4   569.3 3578.42   602.8 3573.64
   627.3 3572.42   634.6 3573.62   641.6 3575.98   671.8 3575.31   680.8 3578.99
   720.9 3577.88   741.8 3579.75   782.3 3575.08   823.7 3578.38   859.3 3575.46
   873.8 3577.59     893 3574.95   916.4 3579.09   956.4 3576.16     995 3578.47
  1253.6 3578.69  1423.5  3589.3  1441.7 3591.28  1455.3 3597.72    1491 3599.99
#Mann= 12 ,-1,0
       0      .1       0  243.82     .06       0  253.82      .1       0
  524.21     .12       0   602.8    .045       0   634.6     .06       0
  689.57     .12       0  735.55     .07       0  855.55     .06       0
  875.55     .12       0 1165.52      .1       0 1265.52     .06       0
#XS Ineff= 2 , 0
          384.69 3580.76
Permanent Ineff=
       F       F
Bank Sta=602.8,634.6
XS Rating Curve= 0 ,0
Exp/Cntr(USF)=0,0
Exp/Cntr=0.3,0.1

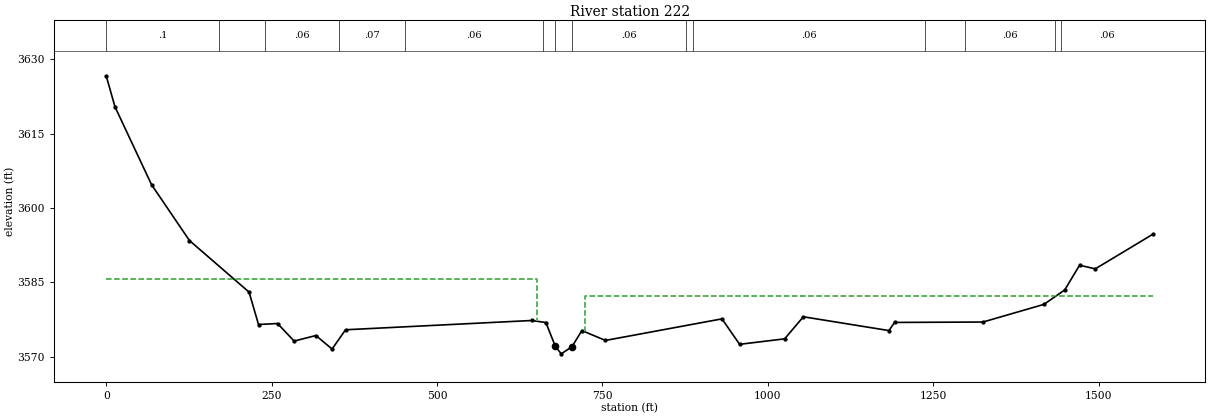
Type RM Length L Ch R = 1 ,222     ,68.6,73.9,78.5
BEGIN DESCRIPTION:
Structure XS 2
END DESCRIPTION:
XS GIS Cut Line= 6
2283416.40577155584747.8626040662283587.72157692584520.905767887
2283578.93615101584342.2687742482283368.08592901583907.390191375
2283297.02752073583513.1537324972283093.08980758 583409.69248289
#Sta/Elev= 30
       0 3626.65    13.2 3620.42    68.5 3604.71   125.8 3593.45   215.9 3583.05
   230.2 3576.52     259 3576.72     284 3573.18   316.9  3574.3   341.4 3571.58
   361.7 3575.46   643.1 3577.33   664.5 3576.92   678.8  3572.1   687.7 3570.61
  703.993572.061   718.9  3575.3   754.5 3573.31   930.6 3577.66   957.2 3572.53
  1025.3 3573.63  1053.6 3578.08  1182.9  3575.3  1191.4 3576.94    1325 3577.02
  1417.2 3580.58  1448.6 3583.49    1471 3588.47  1494.8 3587.74  1582.1 3594.74
#Mann= 14 ,-1,0
       0      .1       0     170     .08       0     240     .06       0
  351.85     .07       0  451.85     .06       0  660.11      .1       0
   678.8    .045       0  703.99     .06       0  876.09     .07       0
  886.09     .06       0 1237.35      .1       0 1297.35     .06       0
 1433.42      .1       0 1443.42     .06       0
#XS Ineff= 2 , 0
          650.46 3585.64   723.2         3582.31
Permanent Ineff=
       F       F
Bank Sta=678.8,703.99
XS Rating Curve= 0 ,0
Exp/Cntr(USF)=0,0
Exp/Cntr=0.3,0.1