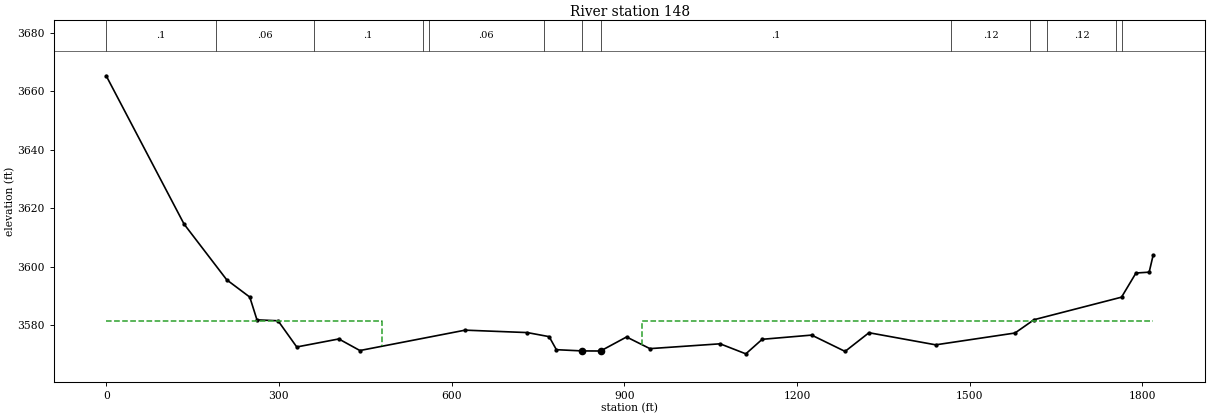
HEC-RAS study LAMBERTRN.prj: LAMBERTRN

--- LAMBERTRN.g01 (geometry) --- (continued)

Type RM Length L Ch R = 1 ,148     ,,,
BEGIN DESCRIPTION:
Structure XS 1
END DESCRIPTION:
XS GIS Cut Line= 5
2283490.48761421584851.2984708122283661.14363297584654.845612002
2283496.53501453583731.7841662082283415.30454149583435.945121722
2283164.30184019583247.467541237
#Sta/Elev= 30
       0 3665.26   135.3 3614.53   209.4 3595.48   249.4 3589.58   261.9 3581.79
   298.5 3581.48     331 3572.52   404.1 3575.26   440.7  3571.3   623.5 3578.27
   731.5 3577.44   769.4 3576.05     782 3571.59   826.7 3571.17  858.673571.139
   903.9 3575.94   944.5 3571.95  1066.4  3573.6  1111.1 3570.17  1139.5 3575.14
  1225.4 3576.58  1283.5    3571    1325 3577.39  1440.9 3573.25  1578.6 3577.29
  1611.7 3581.84  1763.7 3589.55  1788.8 3597.81  1811.7  3598.1  1818.5  3603.8
#Mann= 13 ,-1,0
       0      .1       0     190     .06       0  360.23      .1       0
  550.23     .07       0  560.23     .06       0  760.23      .1       0
   826.7    .045       0  858.67      .1       0 1467.85     .12       0
 1604.64      .1       0 1634.64     .12       0 1754.64     .07       0
 1764.64     .06       0
#XS Ineff= 2 , 0
          479.42 3581.52  931.41         3581.31
Permanent Ineff=
       F       F
Bank Sta=826.7,858.67
XS Rating Curve= 0 ,0
Exp/Cntr(USF)=0,0
Exp/Cntr=0.3,0.1
LCMann Table=0

Chan Stop Cuts=-1
Use User Specified Reach Order=0
Composite Channel Slope=5